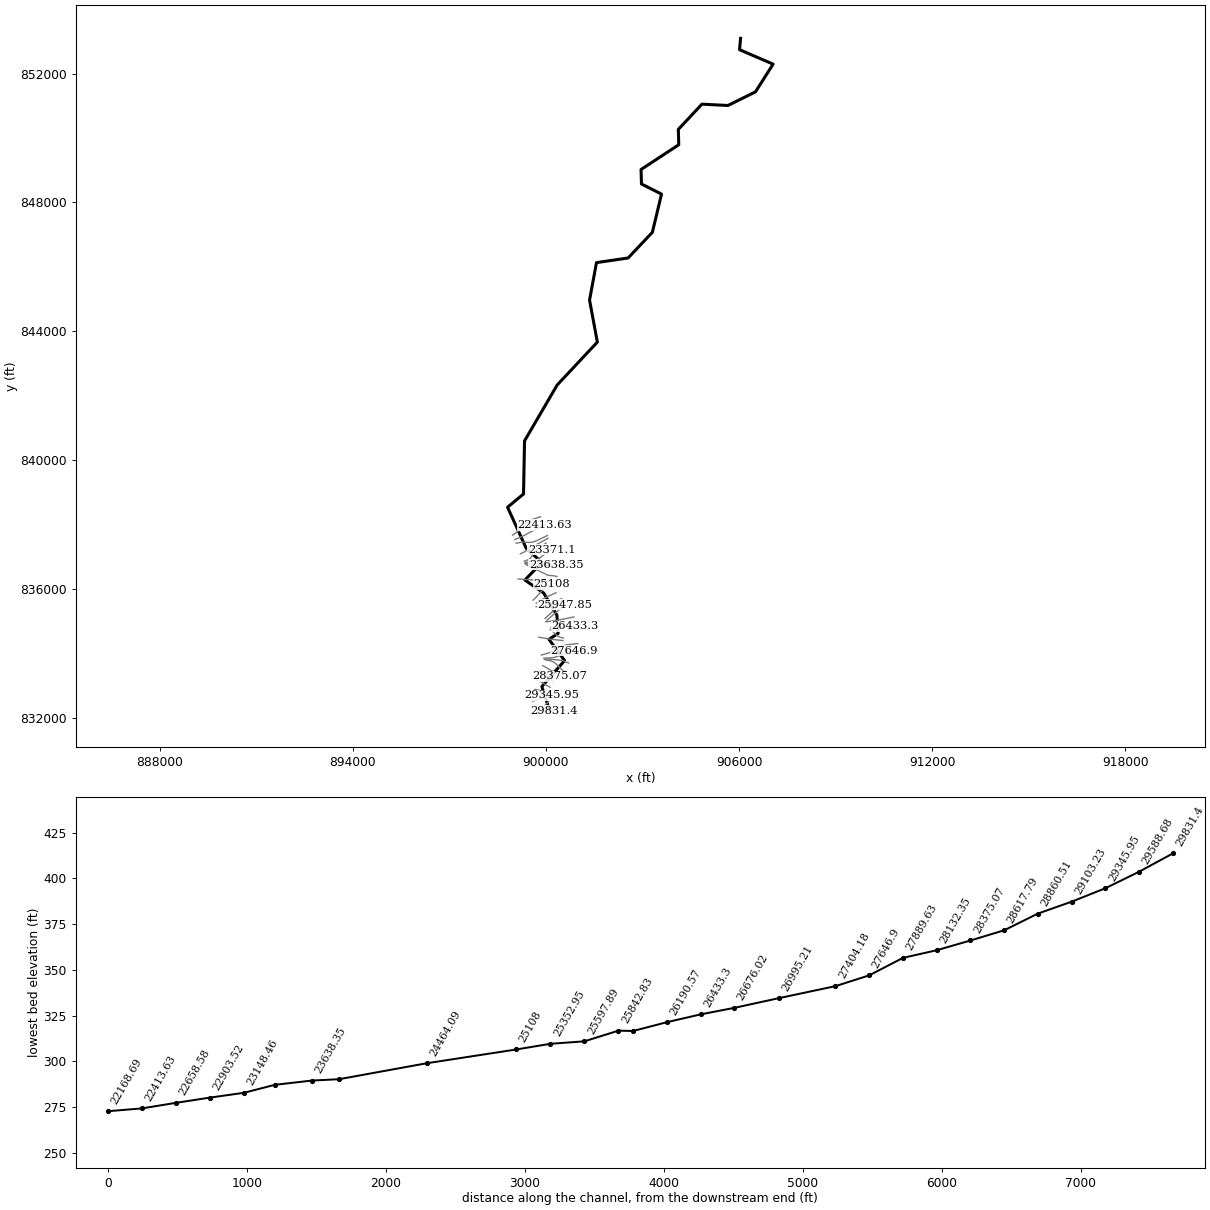
--- 16701_ras.prj (project) ---

Proj Title=16701
Current Plan=p01
Default Exp/Contr=0.3,0.1
English Units
Geom File=g01
Flow File=f01
Plan File=p01
Y Axis Title=Elevation
X Axis Title(PF)=Main Channel Distance
X Axis Title(XS)=Station
BEGIN DESCRIPTION:
RFD model 16701 exported to HEC-RAS
END DESCRIPTION:

--- 16701_ras.p01 (plan) ---

Plan Title=Plan 01
Program Version=4.10
Short Identifier=Plan 01
Geom File=g01
Flow File=f01
Subcritical Flow
Calc Critical at every XS
Secant Critical Depth

--- 16701_ras.f01 (steady flow) ---

Flow Title=Flow 01
Program Version=5.01
Number of Profiles= 6
Profile Names=10yr,25yr,50yr,100yr,100plus,500yr
River Rch & RM=16701,85, 29831.4
 4198.61  5626.3 6783.69 7525.4810987.19 10024.5
River Rch & RM=16701,85,29588.68
 4214.29 5649.17 6812.75 7559.1811036.4110067.38
River Rch & RM=16701,85,29345.95
  4230.7 5672.93 6842.82 7593.9311087.1410111.21
River Rch & RM=16701,85,29103.23
 4264.72 5722.14 6905.05 7665.82 11192.1 10201.7
River Rch & RM=16701,85,28860.51
 4279.33 5743.39 6932.01 7697.0711237.7210241.25
River Rch & RM=16701,85,28617.79
  4286.4  5753.7 6945.11 7712.2611259.89 10260.5
River Rch & RM=16701,85,28375.07
 4358.11 5857.48 7076.43 7864.0411481.49 10451.2
River Rch & RM=16701,85,28132.35
 4361.52 5862.59 7083.02 7871.7811492.7910461.25
River Rch & RM=16701,85,27889.63
 4391.49 5906.77 7139.52 7937.67   1158910545.54
River Rch & RM=16701,85, 27646.9
 4592.82 6204.05 7520.12 8381.98 12237.711112.65
River Rch & RM=16701,85,27404.18
 4600.55 6215.61 7535.02 8399.4912263.2611135.21
River Rch & RM=16701,85,26995.21
 4731.91 6413.52 7791.37  8701.712704.4811526.74
River Rch & RM=16701,85,26676.02
 4735.23 6418.49 7797.79 8709.2412715.4911536.41
River Rch & RM=16701,85, 26433.3
 4738.11 6422.85 7803.45 8715.9312725.2611545.11
River Rch & RM=16701,85,26190.57
 4741.53 6428.09 7810.29 8724.04 12737.111555.75
River Rch & RM=16701,85,25947.85
 4811.37    6535 7950.02 8890.0112979.4211773.36
River Rch & RM=16701,85,25597.89
 5612.47 7701.68 9433.5910612.7915494.6713891.39
River Rch & RM=16701,85,25352.95
 5616.15 7707.23 9440.8110621.3115507.1213902.18
River Rch & RM=16701,85,   25108
 5621.38 7715.13 9451.0510633.4215524.7913917.46
River Rch & RM=16701,85,24464.09
 5638.65 7741.14 9484.7910673.2715582.9813967.73
River Rch & RM=16701,85,23832.33
 5653.06 7763.04 9513.3310707.1115632.3914010.76
River Rch & RM=16701,85,23638.35
 5681.45 7806.52 9570.2710774.8815731.3214097.57
River Rch & RM=16701,85, 23371.1
 5688.33 7816.99 9583.9110791.0515754.9414118.13
River Rch & RM=16701,85,23148.46
 5690.13 7819.72 9587.4710795.27 15761.114123.49
River Rch & RM=16701,85,22903.52
 5772.48 7946.82 9754.61 10994.916052.5614380.71
River Rch & RM=16701,85,22658.58
 5782.97 7962.72 9775.3111019.4316088.3814411.74
River Rch & RM=16701,85,22413.63
 5794.88 7980.96  9799.211047.87 16129.914448.05
River Rch & RM=16701,85,22168.69
 5810.44  8004.7 9830.2211084.7416183.7214494.94
River Rch & RM=16701,85,21923.75
 5820.19 8019.69 9849.89 11108.216217.9714524.99
River Rch & RM=16701,85,21678.81
 5843.56 8055.08 9895.9511162.7616297.6314593.83
River Rch & RM=16701,85,21260.76
 6003.84 8298.2910212.9111538.6216846.3915067.88
River Rch & RM=16701,85, 20903.8
 6031.43  8340.810268.7811605.34 16943.815153.13
River Rch & RM=16701,85,20699.04
 6061.42 8387.1810329.8811678.4617050.5515246.85
River Rch & RM=16701,85,20454.09
    6069 8398.8610345.23 11696.817077.3215270.24
River Rch & RM=16701,85,20209.15
 6075.15 8408.4910358.0111712.1717099.7615290.16
River Rch & RM=16701,85,19964.21
 6096.15 8441.5810402.0411765.2917177.3215359.37
River Rch & RM=16701,85,19719.27
 6101.22 8449.5210412.5711777.9617195.8215375.78
River Rch & RM=16701,85,19474.32
 6112.43 8467.0710435.8511805.9717236.7115412.05
River Rch & RM=16701,85,19229.38
 6117.76 8475.4210446.92 11819.317256.1715429.31
River Rch & RM=16701,85,18984.44
  6130.9 8495.9510474.13   1185217303.9215471.56
River Rch & RM=16701,85,18739.49
 6140.14 8510.6110493.7111875.6917338.5115502.57
River Rch & RM=16701,85,18494.55
  6145.6 8519.3810505.4911890.0217359.4215521.51
River Rch & RM=16701,85,18249.61
 6160.46 8543.0910537.2711928.5817415.7315572.26
River Rch & RM=16701,85,18004.67
 6228.91 8650.1310679.1612099.2617664.9115792.57
River Rch & RM=16701,85,17759.72
 6233.97 8658.3210690.2212112.7617684.6215810.52
River Rch & RM=16701,85,17514.78
 6239.73 8667.6610702.8412128.1717707.1215831.02
River Rch & RM=16701,85,17269.84
 6252.09 8687.7610730.0412161.43 17755.715875.41
River Rch & RM=16701,85, 17024.9
 6345.04 8837.8410932.4612408.3318116.1616202.54
River Rch & RM=16701,85,16779.95
 6348.09 8843.0910939.7812417.47 18129.516215.23
River Rch & RM=16701,85,16535.01
 6350.35 8846.9710945.1612424.1918139.3116224.54
River Rch & RM=16701,85,16290.07
 6382.73 8901.0911019.4612516.0918273.4916349.54
River Rch & RM=16701,85,16045.13
 6395.98 8923.7111050.8312555.1818330.5716403.47
River Rch & RM=16701,85,15800.18
 6417.39 8959.8911100.7712617.2118421.1216488.45
River Rch & RM=16701,85,15555.24
 6453.25 9022.47 11188.512727.4618582.0916642.82
River Rch & RM=16701,85, 15310.3
 6457.31 9029.7211198.7612740.4518601.0516661.24
River Rch & RM=16701,85,15065.36
 6466.21 9045.4211220.8812768.3518641.7916700.57
River Rch & RM=16701,85,14820.41
 6470.62 9053.56 11232.612783.36 18663.716722.31
River Rch & RM=16701,85,14580.65
 6472.13 9056.3711236.6512788.5418671.2716729.83
River Rch & RM=16701,85, 14299.1
 6805.43  9585.111944.0113646.3519923.6817842.07
River Rch & RM=16701,85,14085.59
 6806.65  9587.311947.1513650.3619929.5317847.77
River Rch & RM=16701,85,13970.48
 6807.17 9588.25 11948.513652.0819932.0317850.22
River Rch & RM=16701,85,13476.17
 6816.41 9605.0711972.5813682.8319976.9317894.19
River Rch & RM=16701,85,12981.85
    6820 9611.8811982.4913695.6419995.6317912.91
River Rch & RM=16701,85,12413.18
 6935.59 9815.1412269.0414057.6420524.1618419.43
River Rch & RM=16701,85, 11498.9
  7049.510028.2812578.2314456.6521106.7118998.51
River Rch & RM=16701,85,11004.58
 7058.3710045.2812603.1614489.0821154.0519046.19
River Rch & RM=16701,85,10510.27
 7078.2910083.9712660.2114563.5921262.8419156.46
River Rch & RM=16701,85,10015.95
 7146.5410213.8412850.2114810.4221623.2219518.06
River Rch & RM=16701,85,9521.636
 7150.6310221.7912861.96 14825.821645.6819540.87
River Rch & RM=16701,85, 9027.32
 7226.7110370.5513082.2415114.5522067.2419969.91
River Rch & RM=16701,85,7848.272
 7266.5910447.3213195.2915262.2422282.8620187.73
River Rch & RM=16701,85,7050.055
 7338.4810585.5513398.8415528.22 22671.220579.82
River Rch & RM=16701,85,6555.739
 7341.4910591.4213407.5415539.6322687.8720596.76
River Rch & RM=16701,85,6061.423
 7359.5810626.3913459.1815607.2822786.6320696.79
River Rch & RM=16701,85,5567.106
  7375.910658.3513506.6515669.7122877.7720789.73
River Rch & RM=16701,85, 5072.79
 7385.13 10676.513533.6215705.2122929.6120842.65
River Rch & RM=16701,85,4578.474
 7438.8210782.3113691.2415912.9923232.9721152.99
River Rch & RM=16701,85, 3998.13
 7494.6310894.3813859.5516136.2223558.8821489.59
River Rch & RM=16701,85,3589.842
 7507.8910921.1413899.8616189.7823637.0821570.57
River Rch & RM=16701,85,3399.091
 7509.9510925.2313905.9716197.8623648.8721582.68
River Rch & RM=16701,85,2917.486
 7518.9810943.4613933.4116234.3423702.1321637.85
River Rch & RM=16701,85,2135.695
 7523.4310952.5613947.1916252.7123728.9621665.79
River Rch & RM=16701,85,1665.593
 7525.5910956.9813953.8816261.6423741.9921679.38
River Rch & RM=16701,85,      -0
11340.4117052.12 22186.326351.6438473.3934225.42
Boundary for River Rch & Prof#=16701,85,1
Up Type= 0
Dn Type= 2
Boundary for River Rch & Prof#=16701,85,2
Up Type= 0
Dn Type= 2
Boundary for River Rch & Prof#=16701,85,2
Up Type= 0
Dn Type= 2
Boundary for River Rch & Prof#=16701,85,2
Up Type= 0
Dn Type= 2
Boundary for River Rch & Prof#=16701,85,2
Up Type= 0
Dn Type= 2
Boundary for River Rch & Prof#=16701,85,2
Up Type= 0
Dn Type= 2

--- 16701_ras.g01 (geometry) ---

Geom Title=16701
Program Version=4.10

River Reach=16701,85
Reach XY= 30
900114.527195624 832221.76580848899874.846356055  832966.8364642
900580.732463418833775.080951427900094.264833471834432.316089531
900379.327699106834616.012509223900341.746975796835181.585286276
899931.534992885835870.225344296899347.645988287836274.610255341
899877.692490451836822.292821778899393.014778572837250.484534032
898808.089086424838535.241198291899304.511582274838945.587623149
899335.865869093840593.652590827900350.716895724842330.601782699
901598.484549886843661.760092006901355.712927348 844964.74935642
901571.080510399 846129.17685717902553.759089051846273.122405935
903307.436556679847070.360090295903591.535412765848256.592859238
902968.865715802848569.923868468902955.772937398849020.101203907
904126.988280305849788.040702534904114.075483061850265.010615065
904847.685133751851048.456006523905654.763789415851007.272504864
906511.102752831851430.851915814907058.003168829852291.595643485
906016.143886581852739.374446846906047.613627539853092.224738594

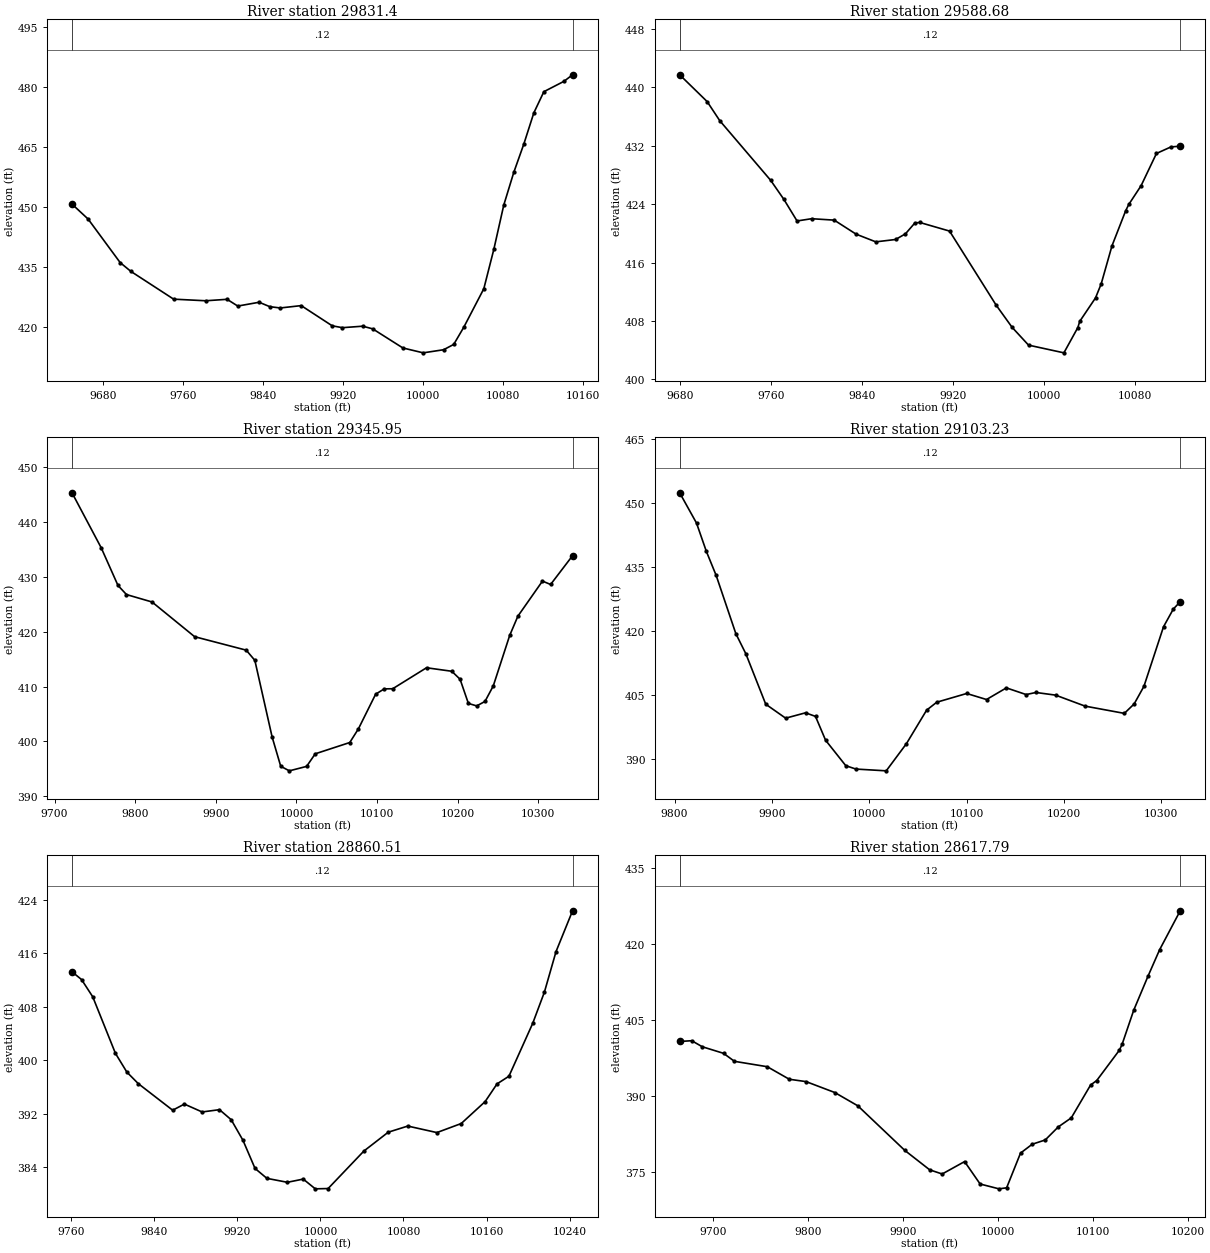
Type RM Length L Ch R = 1 , 29831.4,242.721600,242.721600,242.721600
XS GIS Cut Line= 6
899779.919236092832134.824115061899963.920561348832204.743192923
900049.181624848832227.274265118900083.921707582832228.408484741
900173.188782603 832214.68327573900263.599296492 832220.45095552
#Sta/Elev= 30
9648.707450.7877 9664.84447.05189696.933436.17029707.631 433.9819750.421427.0429
9782.514426.64069803.909427.00499814.607425.31699836.002426.26869846.676425.1642
9857.155424.84229878.113425.43149909.152420.38189919.362419.91789939.664420.2871
9949.669419.62329979.859414.850810000.21413.631110020.58414.401910030.76415.7347
10040.83 420.02610060.87  429.6410070.87439.456610080.87450.565110090.87458.7147
10100.91465.780110110.95473.592310120.99478.877310141.08 481.46410149.71483.1005
#Mann= 3 , 0 , 0
9648.707    0.12       09648.707    0.12       010149.71    0.12       0
#XS Ineff= 2 , 0
       0                               0
Bank Sta=9648.707,10149.71
Exp/Cntr=0.3,0.1

Type RM Length L Ch R = 1 ,29588.68,242.721500,242.721500,242.721500
XS GIS Cut Line= 6
899733.310966063832231.483350657899800.917816293 832264.53007612
899865.819370697832302.346262111899909.330604538832333.075993568
899942.961742486832361.170320119900081.392084399832494.310011205
#Sta/Elev= 30
9679.754441.70459703.888438.03839715.021435.41269759.731427.24889771.305424.6466
9782.879421.68999795.666421.9998 9815.53421.80529834.722419.88659852.056 418.831
9869.391419.15349878.088419.92689886.391421.41979890.777421.48099916.838420.3057
 9957.75410.17219971.744407.13679986.225404.691610017.29403.636410029.54407.1004
10031.18407.940210045.08 411.16410050.03413.070410059.52418.2857 10071.5423.0705
10074.26423.949510085.11426.523710098.58430.930710111.32431.828610119.46431.9297
#Mann= 3 , 0 , 0
9679.754    0.12       09679.754    0.12       010119.46    0.12       0
#XS Ineff= 2 , 0
       0                               0
Bank Sta=9679.754,10119.46
Exp/Cntr=0.3,0.1

Type RM Length L Ch R = 1 ,29345.95,242.721600,242.721600,242.721600
XS GIS Cut Line= 6
899590.354568294832515.095825393899752.148213217832568.103360923
899952.252114443832644.665652102900029.534079989832669.201412857
900089.414930596 832683.78136449900182.029319302832698.780302498
#Sta/Elev= 30
9721.578445.37479757.759435.34719778.646428.45019789.184426.79319820.891 425.437
9873.736419.10159937.737416.64489948.443414.78499969.854400.8105 9980.56395.4454
9991.266394.613410012.67395.424710023.38397.722610066.22399.782510076.93402.2751
10098.34408.607610108.99 409.57610119.49409.599410161.45413.431110192.82412.7916
10203.11411.3302 10213.4406.9223 10223.7 406.46710233.99407.279510244.28410.1114
10264.68419.338310274.85422.853110305.33429.252710315.42428.634410342.68433.8915
#Mann= 3 , 0 , 0
9721.578    0.12       09721.578    0.12       010342.68    0.12       0
#XS Ineff= 2 , 0
       0                 10169.6       0
Bank Sta=9721.578,10342.68
Exp/Cntr=0.3,0.1

Type RM Length L Ch R = 1 ,29103.23,242.721500,242.721500,242.721500
XS GIS Cut Line= 6
899657.873406471832878.836862046899714.074855821832870.573663492
899796.354106157832853.074273507899925.337703845832817.285061005
899998.846712056832802.870138449900162.044738105832782.510638211
#Sta/Elev= 30
9805.174452.30879822.485445.22699832.593438.6064  9842.7432.96349862.926419.3377
 9873.15414.65999893.597402.85719914.044399.58919934.492400.84399944.715400.0033
9955.074394.43019975.834388.47279986.214387.687810017.37387.271110038.12393.6296
10058.86401.466910069.24403.3193   10100405.362910120.38403.952310140.76406.6733
10161.08405.114110171.17405.598810191.35404.978110221.62402.407110261.94400.7116
10272.01402.912510282.07407.035810302.19 420.97210312.25425.108410319.34426.8292
#Mann= 3 , 0 , 0
9805.174    0.12       09805.174    0.12       010319.34    0.12       0
#XS Ineff= 2 , 0
       0                 10107.4       0
Bank Sta=9805.174,10319.34
Exp/Cntr=0.3,0.1

Type RM Length L Ch R = 1 ,28860.51,242.721600,242.721600,242.721600
XS GIS Cut Line= 6
899706.462665325833177.504037325899790.310341789833140.518836747
 899852.05682438833108.417325577900039.510593686832995.403380563
900096.189179014832963.728928388900129.186413489832946.953193186
#Sta/Elev= 30
 9760.75413.23179769.946412.06629780.716409.49019802.581401.03119813.579  398.23
9824.578 396.503  9857.7392.52979868.971393.44469886.058392.26799902.783392.6088
9914.054391.11039925.423388.02439937.028 383.822 9948.45382.33879968.157381.7499
9983.448382.22929995.053380.771410007.41380.815910041.86386.4223 10065.3389.2394
10084.13390.158510112.18389.184910135.61390.538410158.64393.8167 10170.1396.4643
10181.56397.610410204.47405.520110215.71410.181510226.93416.254610242.85422.3522
#Mann= 3 , 0 , 0
 9760.75    0.12       0 9760.75    0.12       010242.85    0.12       0
#XS Ineff= 2 , 0
       0                10100.01       0
Bank Sta=9760.75,10242.85
Exp/Cntr=0.3,0.1

Type RM Length L Ch R = 1 ,28617.79,242.721500,242.721500,242.721500
XS GIS Cut Line= 6
899803.509537708833439.240009768899901.637574888833386.894049394
899959.561214284 833348.87724459900055.733833238833272.596767833
900137.122584972833196.504022586900221.842343575833123.812505189
#Sta/Elev= 30
9665.173 400.7349677.884400.88219688.946399.69169711.302398.39549722.807396.8146
9757.322395.75149780.485393.2773 9798.14392.81149828.331390.65899852.563388.0349
9901.972379.23749928.127375.4048 9941.28374.58419964.854377.03329981.196372.6065
   10001371.654210009.05371.856610023.67378.704110035.95380.453510049.66381.2999
10063.36383.870910077.06385.658810097.37392.141610103.81393.022310127.61399.0056
10130.47400.154410142.73406.9032   10158413.725210169.93418.822610191.62426.5203
#Mann= 3 , 0 , 0
9665.173    0.12       09665.173    0.12       010191.62    0.12       0
#XS Ineff= 2 , 0
       0                10121.55       0
Bank Sta=9665.173,10191.62
Exp/Cntr=0.3,0.1

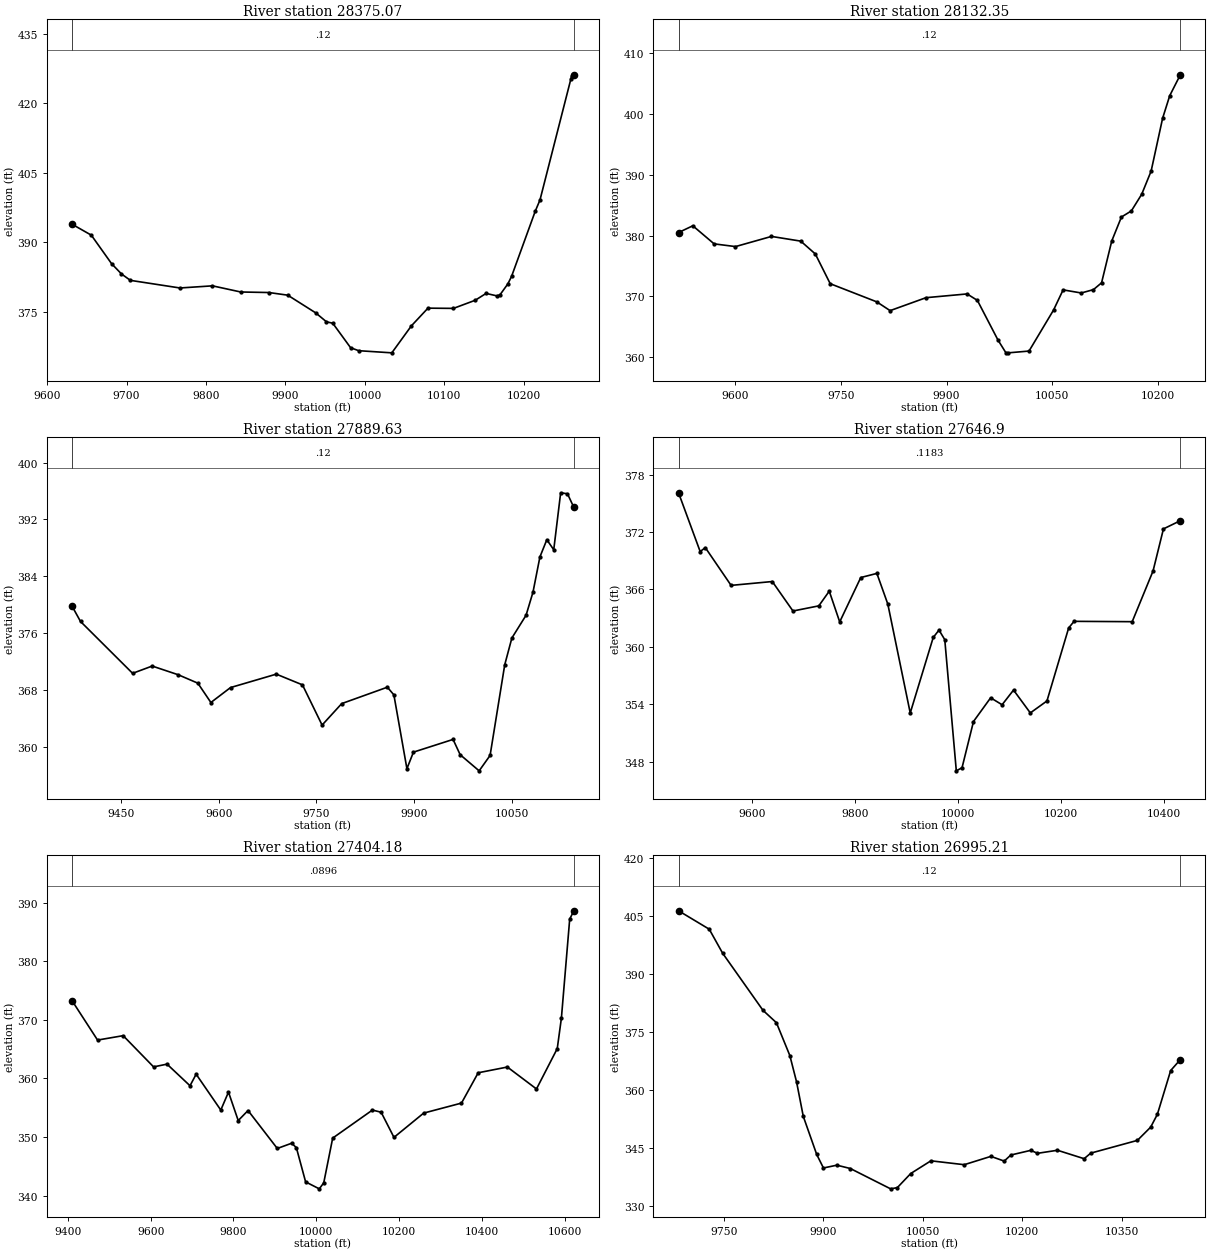
Type RM Length L Ch R = 1 ,28375.07,242.721600,242.721600,242.721600
XS GIS Cut Line= 6
899898.013207612833614.503578421899994.955774598833569.291470156
900177.049016549 833458.15162043900258.314723799833432.444465994
 900291.56499627833406.952636085900426.820207397833282.596546806
#Sta/Elev= 30
9631.367393.86559655.596391.50379681.091385.34939693.616383.11179704.822381.7334
9767.231380.08649808.211380.5481 9843.75379.21979879.288379.1018 9902.98  378.53
9938.075374.71879951.774372.77189959.669372.46599982.116 367.1779992.284366.5294
10034.05366.065610058.68371.897610079.55375.724210111.67375.674710139.06377.4281
10152.76378.910810166.46378.374510170.19 378.59210180.16380.962610184.82382.5767
10214.64 396.66210220.64 399.11310259.69425.360910260.86425.9273 10263.3426.1711
#Mann= 3 , 0 , 0
9631.367    0.12       09631.367    0.12       0 10263.3    0.12       0
#XS Ineff= 2 , 0
       0                10113.21       0
Bank Sta=9631.367,10263.3
Exp/Cntr=0.3,0.1

Type RM Length L Ch R = 1 ,28132.35,242.721600,242.721600,242.721600
XS GIS Cut Line= 6
899974.857699742833797.098439858900122.538925267833771.827757613
900177.346962847833755.320498009900255.592268221833718.949290373
900319.990667517833669.889972464900556.345254838833428.512181401
#Sta/Elev= 30
9519.244 380.4859539.524381.59479569.777378.6274 9600.15378.18279651.258379.8487
9692.862379.07639713.531376.97229734.697372.09299800.812369.11539819.758367.6747
9870.739369.79939929.113370.41589943.732369.35219972.969362.85279984.071360.7883
9987.587360.751110017.08361.043310051.95367.780110065.49371.079510091.26370.5717
10108.57371.120310120.11372.239210134.56379.096310148.32383.033110162.42384.0315
 10177.1386.758810190.49390.559610206.82399.232410216.96402.944210231.98406.3664
#Mann= 3 , 0 , 0
9519.244    0.12       09519.244    0.12       010231.98    0.12       0
#XS Ineff= 2 , 0
       09807.451                       0
Bank Sta=9519.244,10231.98
Exp/Cntr=0.3,0.1

Type RM Length L Ch R = 1 ,27889.63,242.721500,242.721500,242.721500
XS GIS Cut Line= 6
899952.043934643833826.095157452900161.569218367833812.524822846
900520.580281702833777.832776994900551.555277158833766.377231403
900631.739746312833724.336078093900704.367879738833698.995142599
#Sta/Elev= 30
9374.313379.7717 9387.28377.62049467.407370.31229497.491371.33839537.603370.1097
9567.687368.92699587.753366.20389617.924368.30769688.322370.1992 9728.55368.6874
9758.721363.02189788.892366.0486 9859.07368.35959869.093367.27949889.139356.8805
9899.162359.21119960.106361.00349970.994358.849910000.19356.577410017.02358.7477
10039.54371.522310050.51375.288510072.34378.496410082.98 381.75110093.61386.7076
10104.25389.135210114.88387.720510125.52395.746310136.01395.605810145.81393.6854
#Mann= 3 , 0 , 0
9374.313    0.12       09374.313    0.12       010145.81    0.12       0
#XS Ineff= 2 , 0
       09708.651                       0
Bank Sta=9374.313,10145.81
Exp/Cntr=0.3,0.1

Type RM Length L Ch R = 1 , 27646.9,242.721600,242.721600,242.721600
XS GIS Cut Line= 6
899932.983971188833850.320740218900112.255465854833854.846221375
900268.661449914833873.548345828900379.344456911833912.853429951
900618.198891066834025.480119187900867.519175117834079.025041716
#Sta/Elev= 30
9457.628376.09949499.652369.95299509.656370.36519559.677366.41769639.717366.8201
9679.852363.73869730.053364.2762 9750.34365.81419770.627362.59799811.529367.2381
9842.815367.66939864.064364.46169907.589353.07569952.262360.97359963.465361.7449
9974.668 360.7419997.075347.027410008.21347.353610030.43352.184710063.76354.6645
10085.98353.9367 10108.2355.4733 10140.8353.0826 10173.1354.332510215.26361.9667
10225.74362.658410338.65362.621510379.15367.922710399.32372.323410432.12  373.18
#Mann= 3 , 0 , 0
9457.628  0.1183       09457.628  0.1183       010432.12  0.1183       0
#XS Ineff= 2 , 0
       09826.925        10161.59       0
Bank Sta=9457.628,10432.12
Exp/Cntr=0.3,0.1

Type RM Length L Ch R = 1 ,27404.18,408.969100,408.969100,408.969100
XS GIS Cut Line= 6
899854.281765285833944.342279002 900096.44335178834013.032717674
900338.928498573 834157.52937992900537.439468639834237.019635141
900698.588392957834271.653889854900995.038964271834302.405173197
#Sta/Elev= 30
 9410.07373.28089471.654366.55889533.511367.31199606.974361.97799639.493362.4464
9695.018358.75449709.845 360.7299769.382354.6016 9787.99357.66949811.496352.8059
9835.212354.52259905.922348.03849940.637348.93389951.968348.17969974.319342.3298
10007.35341.141710018.14342.170410039.72349.808710135.72354.600710156.79354.2298
10187.79349.933410259.59354.083110350.93355.792110391.31360.972510461.75361.9518
10532.09358.205710582.28365.0971 10592.3370.307710612.35387.222410622.41388.6483
#Mann= 3 , 0 , 0
 9410.07  0.0896       0 9410.07  0.0896       010622.41  0.0896       0
#XS Ineff= 2 , 0
       09775.797        10140.23       0
Bank Sta=9410.07,10622.41
Exp/Cntr=0.3,0.1

Type RM Length L Ch R = 1 ,26995.21,319.195500,319.195500,319.195500
XS GIS Cut Line= 4
 899779.28094742834498.530450781900160.569527357834434.173639977
900525.075155843834396.348620214900529.515693724834396.421815544
#Sta/Elev= 30
9681.206406.44119727.572401.67759747.855395.44999808.703380.70339828.986377.5067
9849.269369.00279859.411362.19529869.552353.28269889.835343.43379899.976339.9449
9920.259  340.679940.542339.807510001.39 334.55210011.53334.865810031.82 338.517
10062.24341.797610112.56340.793210152.77342.945510172.88341.728710182.93343.2961
10213.09 344.50610223.15 343.73610253.31344.525710293.52342.345610303.58343.7841
10373.95347.077710394.06350.513110404.11353.806310424.22365.134210438.79367.9658
#Mann= 3 , 0 , 0
9681.206    0.12       09681.206    0.12       010438.79    0.12       0
#XS Ineff= 2 , 0
       0                               0
Bank Sta=9681.206,10438.79
Exp/Cntr=0.3,0.1

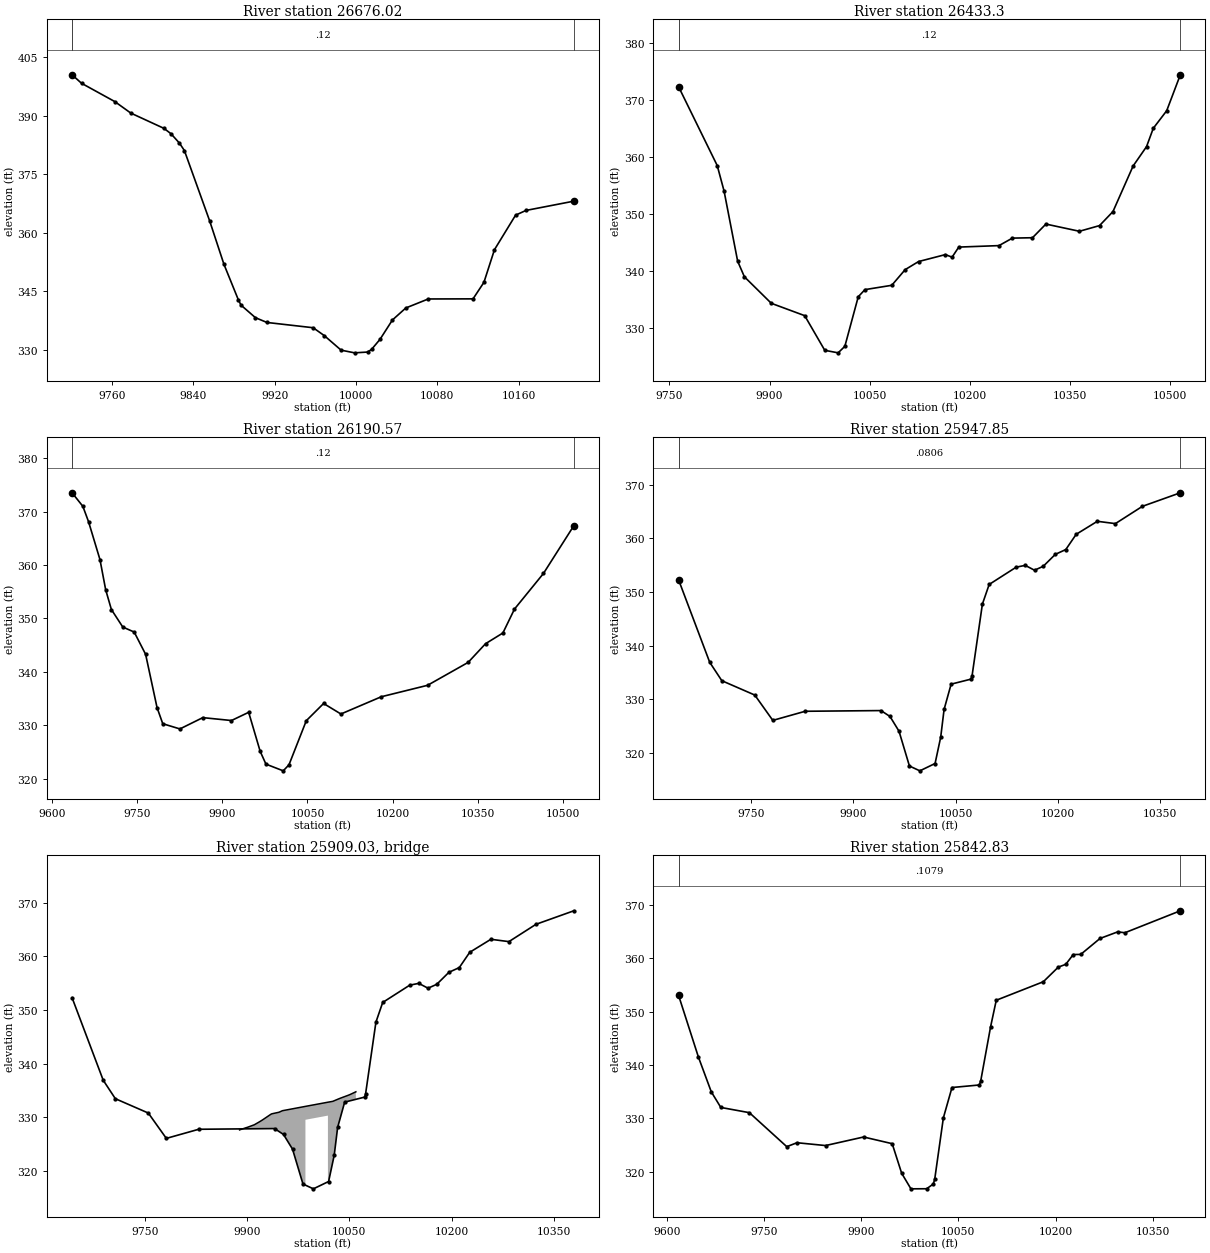
Type RM Length L Ch R = 1 ,26676.02,242.721600,242.721600,242.721600
XS GIS Cut Line= 6
900137.336824098834738.760455041900186.712317519834704.933023505
900326.249773052834571.431535455 900385.74830351834525.597389592
900452.472900698 834493.43818776900541.486473527 834474.88754333
#Sta/Elev= 30
9720.749400.52289730.038398.34729762.789 393.6539778.525390.70659811.073386.7985
    9818385.4275 9826.36383.01049831.221381.1122 9856.04363.11489870.136351.9598
9884.232342.90379886.933341.49029901.122338.27799912.424337.05499957.877335.7048
9968.809333.68859985.379329.95739998.567329.271110011.36329.469610015.31330.1494
10023.64332.728810035.87337.695910049.02340.7664 10071.1343.075310115.14343.1032
10125.85 347.33510136.22355.707910156.98364.549610167.23365.762110214.31368.1392
#Mann= 3 , 0 , 0
9720.749    0.12       09720.749    0.12       010214.31    0.12       0
#XS Ineff= 2 , 0
       0                               0
Bank Sta=9720.749,10214.31
Exp/Cntr=0.3,0.1

Type RM Length L Ch R = 1 , 26433.3,242.721500,242.721500,242.721500
XS GIS Cut Line= 6
900158.657208717834811.001655052900237.963151236834792.436553958
900295.786047848834784.910373795900354.467305252834784.087060681
900775.084493325834820.487196091900905.263232722834835.202284156
#Sta/Elev= 30
9763.705372.3429 9821.65 358.516 9831.89 354.0639852.262341.75659862.346339.0292
9902.684334.38129952.695332.21699982.745326.1463 10002.8325.703110012.84 326.846
10032.92335.532910042.96336.779410083.11337.535310103.19 340.28110123.27341.6983
10163.42 342.91510173.46342.4652 10183.5344.231110243.73  344.4910263.81 345.803
10293.92345.8696   10314348.2628 10364.2347.000610394.34347.995610414.46350.4529
10444.66358.441210464.78361.835710474.85365.041210494.97368.124910515.37374.4193
#Mann= 3 , 0 , 0
9763.705    0.12       09763.705    0.12       010515.37    0.12       0
#XS Ineff= 2 , 0
       0                 10094.3       0
Bank Sta=9763.705,10515.37
Exp/Cntr=0.3,0.1

Type RM Length L Ch R = 1 ,26190.57,242.721600,242.721600,242.721600
XS GIS Cut Line= 6
899996.076247715834979.228051156900111.622816471834991.420896295
900218.719738729835004.933923193 900308.60837571835018.244304261
900558.235780237835064.028840821900867.480130287835128.457890469
#Sta/Elev= 30
9634.961373.5464 9653.99371.00589664.045368.11699684.156361.02399694.212355.3734
9704.267351.67439724.378348.3857 9744.49347.44989764.632343.27979784.791333.2873
 9794.87330.26979825.108 329.2959865.444 331.4129915.989330.87059946.316332.4087
9966.608325.09349976.762322.700110007.24321.441810017.41322.578910047.92330.8399
10078.43334.063310108.94332.093510180.13335.323510261.74337.470310333.24341.7606
10363.89345.262310394.53347.274510414.96351.755710466.03 358.42710519.64367.3861
#Mann= 3 , 0 , 0
9634.961    0.12       09634.961    0.12       010519.64    0.12       0
#XS Ineff= 2 , 0
       0                10077.75       0
Bank Sta=9634.961,10519.64
Exp/Cntr=0.3,0.1

Type RM Length L Ch R = 1 ,25947.85,105.022600,105.022600,105.022600
XS GIS Cut Line= 2
900030.427274001835023.461718709900587.045655322 835504.91120705
#Sta/Elev= 30
9643.435 352.2959689.146336.88949706.931333.45099755.255330.77569781.699 326.049
9829.219 327.749 9940.36327.87989953.581326.77589966.794324.0305 9982.08317.5373
9997.366316.637710019.69318.006510027.94322.926110032.91328.093510043.22332.8098
10072.58 333.751 10073.8334.240810089.08347.737810099.02351.405610138.69354.6327
10151.91354.965710165.51354.062310178.35354.795910196.08357.026110211.37357.9136
10226.66360.761110257.68363.188110284.13 362.75410323.79 365.98110379.38368.5073
#Mann= 3 , 0 , 0
9643.435  0.0806       09643.435  0.0806       010379.38  0.0806       0
#XS Ineff= 2 , 0
       0                               0
Bank Sta=9643.435,10379.38
Exp/Cntr=0.3,0.1

Type RM Length L Ch R = 3 ,25909.03,,,
BEGIN DESCRIPTION:
END DESCRIPTION:
Bridge Culvert--1,0,-1,-1, 0
Deck Dist Width WeirC Skew NumUp NumDn MinLoCord MaxHiCord MaxSubmerge Is_Ogee
44.511300,16.000000,2.6,0, 20, 20, , , 0.95, 0, 0,0,,
 9889.06 9898.61 9900.73 9910.71 9918.50 9922.80 9934.90 9936.27 9947.00 9951.83
 9985.69 9985.6910018.6910018.6910025.8110033.6910036.9610047.9910050.9510059.67
  327.63  328.04  328.12  328.59  329.16  329.50  330.54  330.63  330.93  331.21
  332.02  332.02  332.80  332.80  332.96  333.38  333.55  334.07  334.22  334.74
 -672.37 -671.96 -671.88 -671.41 -670.84 -670.50 -669.46 -669.37 -669.07 -668.79
 -667.98  329.52  330.30 -667.20 -667.04 -666.62 -666.45 -665.93 -665.78 -665.26
 9889.06 9898.61 9900.73 9910.71 9918.50 9922.80 9934.90 9936.27 9947.00 9951.83
 9969.20 9969.2010002.2010002.2010025.8110033.6910036.9610047.9910050.9510059.67
  327.63  328.04  328.12  328.59  329.16  329.50  330.54  330.63  330.93  331.21
  331.62  331.62  332.41  332.41  332.96  333.38  333.55  334.07  334.22  334.74
 -672.37 -671.96 -671.88 -671.41 -670.84 -670.50 -669.46 -669.37 -669.07 -668.79
 -668.38  329.12  329.91 -667.59 -667.04 -666.62 -666.45 -665.93 -665.78 -665.26
BR Coef=-1 , 0 , 0 ,, 0 ,,,0.8,0,1,0,
WSPro=,,,, 1 ,,,, 0 ,,,, 0 ,,,,-1 ,-1 ,-1 , 0 , 0 , 0 , 0 , 0
BC Design=,, 0 ,, 0 ,,,,,,

Type RM Length L Ch R = 1 ,25842.83,244.942600,244.942600,244.942600
XS GIS Cut Line= 6
899972.506114421835080.592815045900233.557715694835322.881738036
900279.021553915835380.817799687900320.431002951835417.131266428
900468.474214602835509.425908719900571.793413289835560.258633901
#Sta/Elev= 30
9617.949353.05769648.638341.49229668.527334.97469683.227332.05859727.327331.0788
9785.072324.71579800.826325.45329844.926324.92419903.726326.52619947.826325.2752
9962.436319.74179976.754316.821910001.04316.839510011.39 317.73310013.57318.6924
10026.85330.106110040.14335.787410082.42336.263410084.55337.041210099.72347.1381
10108.51352.1218 10181.2355.588510204.28358.323510215.83358.847610227.37360.6786
10238.91360.700210268.69 363.68710295.97364.921210307.12364.7587 10392.7  368.87
#Mann= 3 , 0 , 0
9617.949  0.1079       09617.949  0.1079       0 10392.7  0.1079       0
#XS Ineff= 2 , 0
       09747.818                       0
Bank Sta=9617.949,10392.7
Exp/Cntr=0.3,0.1

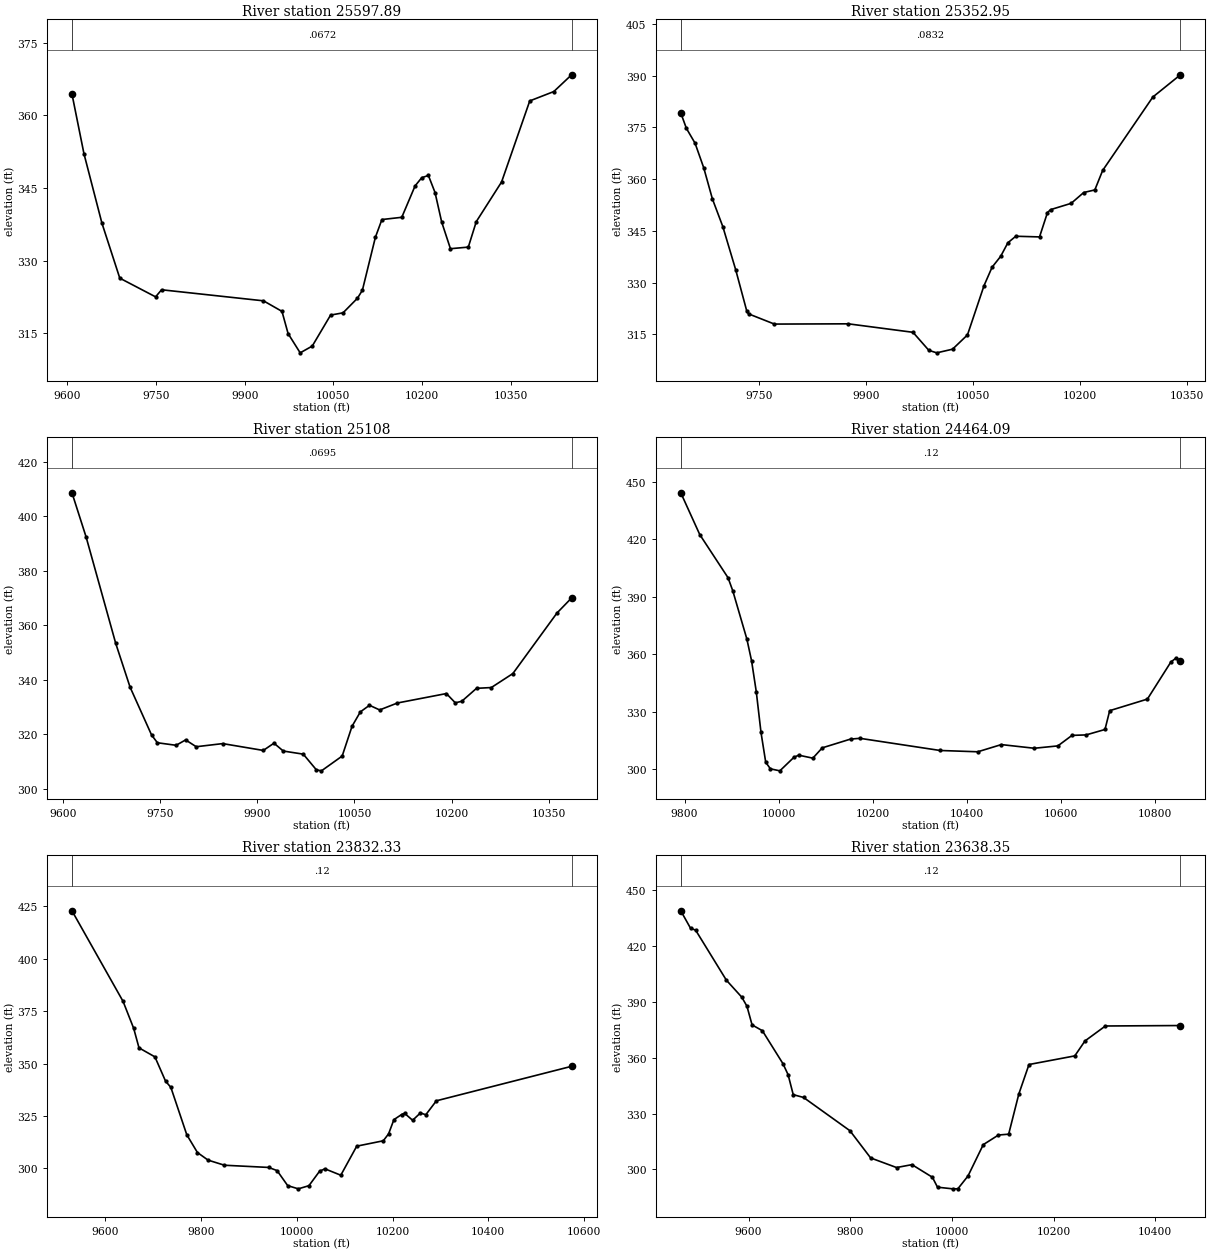
Type RM Length L Ch R = 1 ,25597.89,244.942600,244.942600,244.942600
XS GIS Cut Line= 6
899694.866957715835445.359635866899997.070291594835485.916497122
 900111.82301485835514.772012525900211.832880978835555.412744784
900397.068589284835650.792134108900492.357405749835694.517069018
#Sta/Elev= 30
9608.058364.43179628.371352.0886 9658.64337.80259688.909326.41669749.447322.5569
9759.537  324.029931.853321.73719963.101319.56019973.429314.97729993.853311.0008
10014.26312.3957 10045.3318.794710066.32319.257910090.66322.267510099.04323.9222
10121.04334.864810132.05338.516110165.63338.978810188.12345.460910199.37347.1557
10210.62347.616710221.86344.092810233.11  337.9910247.89332.4975 10278.1332.8261
10291.58338.085610334.34 346.26910381.98363.003210422.66364.936110452.76368.3989
#Mann= 3 , 0 , 0
9608.058  0.0672       09608.058  0.0672       010452.76  0.0672       0
#XS Ineff= 2 , 0
       0 9743.97                       0
Bank Sta=9608.058,10452.76
Exp/Cntr=0.3,0.1

Type RM Length L Ch R = 1 ,25352.95,244.942600,244.942600,244.942600
XS GIS Cut Line= 6
899698.518827775835551.612537148899825.776356748835637.376045035
 899891.98692009835677.933903195899951.327720033835710.829694668
900195.907389145835827.388905643900314.379238887835880.576652989
#Sta/Elev= 30
9640.726379.20759648.594374.72879660.735370.42839672.875363.29939685.015354.2755
9699.607346.2467 9717.65333.73179733.216321.71239735.712320.94139771.836317.9845
 9875.28318.05999965.947315.59899988.136310.37189999.224309.646310021.33310.7042
10042.24314.8423 10065.5329.167810076.71334.474210088.76337.631210098.86341.5651
10109.93343.450610143.16343.255410154.24350.289510158.54351.157710187.47352.9913
10205.07356.1316 10220.6356.875610231.58362.530710301.86383.815210340.49 390.262
#Mann= 3 , 0 , 0
9640.726  0.0832       09640.726  0.0832       010340.49  0.0832       0
#XS Ineff= 2 , 0
       0                               0
Bank Sta=9640.726,10340.49
Exp/Cntr=0.3,0.1

Type RM Length L Ch R = 1 ,   25108,643.914000,643.914000,643.914000
XS GIS Cut Line= 6
899599.425394477835650.352336089899701.659110477835747.893915425
899937.076202372836008.370637499900016.303571391836068.730246879
900075.591716882 836101.56056548900179.763616408836142.398071126
#Sta/Elev= 30
9613.495408.62959635.425392.34129681.147 353.3099703.275 337.2819736.488319.7214
9745.463316.86229774.427315.92929789.119 317.9039805.477315.40159846.428316.5513
 9909.11314.04399925.629316.70149940.013313.82119970.915312.67529991.218306.8965
    9999 306.55210031.01311.980410046.28322.930910059.12 328.201 10073.2330.6181
10088.92328.906910116.41331.463110192.01334.923310205.78331.530410215.72332.0717
10238.58336.841110261.44337.127910294.75342.263410362.87364.481110385.53370.0321
#Mann= 3 , 0 , 0
9613.495  0.0695       09613.495  0.0695       010385.53  0.0695       0
#XS Ineff= 2 , 0
       0                               0
Bank Sta=9613.495,10385.53
Exp/Cntr=0.3,0.1

Type RM Length L Ch R = 1 ,24464.09,631.761700,631.761700,631.761700
XS GIS Cut Line= 2
899134.717479943836307.110706529900195.131326088836237.659267969
#Sta/Elev= 30
9791.998444.39359832.367422.54999892.496399.99869902.517393.22839932.581367.9215
9942.603356.52229952.624340.32429962.645319.07669972.667303.51619982.688300.0758
10002.73299.0319 10032.8306.139910042.82307.218410072.88305.660610092.92311.0545
10153.05  315.63 10173.1316.029510343.46309.676710423.63308.992110473.74312.7546
10543.89 310.837   10594312.073310624.06317.565110654.12317.817110694.21320.6532
10704.23330.4891 10784.4336.536810834.51  355.9810844.53357.827210854.68356.6022
#Mann= 3 , 0 , 0
9791.998    0.12       09791.998    0.12       010854.68    0.12       0
#XS Ineff= 2 , 0
       0                               0
Bank Sta=9791.998,10854.68
Exp/Cntr=0.3,0.1

Type RM Length L Ch R = 1 ,23832.33,193.980000,193.980000,193.980000
XS GIS Cut Line= 4
899378.766674836836752.769482429900069.970592672836421.139501431
900255.500084147836404.646638921900343.738535932836383.785984705
#Sta/Elev= 30
9530.499422.73639637.236379.58639659.418366.7324 9670.51357.44999703.784353.1534
9725.967341.60219737.058 338.6239770.332316.05299792.515307.60749814.698303.9903
9848.987301.54669941.456300.49699958.887298.99019981.069 291.83610003.25290.3059
10025.44 291.81210047.62298.682510058.71299.847210091.98296.793110125.26310.6265
10180.71313.191810191.81316.5005 10202.9323.263410218.87 325.68510225.08326.3003
10241.98322.955610258.35326.469610269.45325.579210291.63332.235810574.07348.6679
#Mann= 3 , 0 , 0
9530.499    0.12       09530.499    0.12       010574.07    0.12       0
#XS Ineff= 2 , 0
       0                               0
Bank Sta=9530.499,10574.07
Exp/Cntr=0.3,0.1

Type RM Length L Ch R = 1 ,23638.35,267.244100,267.244100,267.244100
XS GIS Cut Line= 6
899345.978372792836792.257229795899514.026176768836769.078922645
899777.179073194836722.241691588899827.734437633836715.891586081
  900124.1954972836723.220694576900321.327101741836747.690793591
#Sta/Elev= 30
 9466.52439.01669485.674429.64889495.744428.59999556.282401.70929586.611 392.568
9596.721387.72739606.831377.6821 9627.05 374.5669667.555356.86239677.687350.9434
9687.818340.1904 9708.08  338.699799.402 320.8049840.152306.17659891.089301.0208
9921.457302.57179961.714295.78449971.715290.455210001.72289.570710011.72289.5914
10031.72296.474710061.73313.318810091.73318.500810111.73318.946210131.74340.5582
10151.74356.388310241.84361.0244 10261.9369.055510302.07377.093610449.74377.3401
#Mann= 3 , 0 , 0
 9466.52    0.12       0 9466.52    0.12       010449.74    0.12       0
#XS Ineff= 2 , 0
       0                               0
Bank Sta=9466.52,10449.74
Exp/Cntr=0.3,0.1

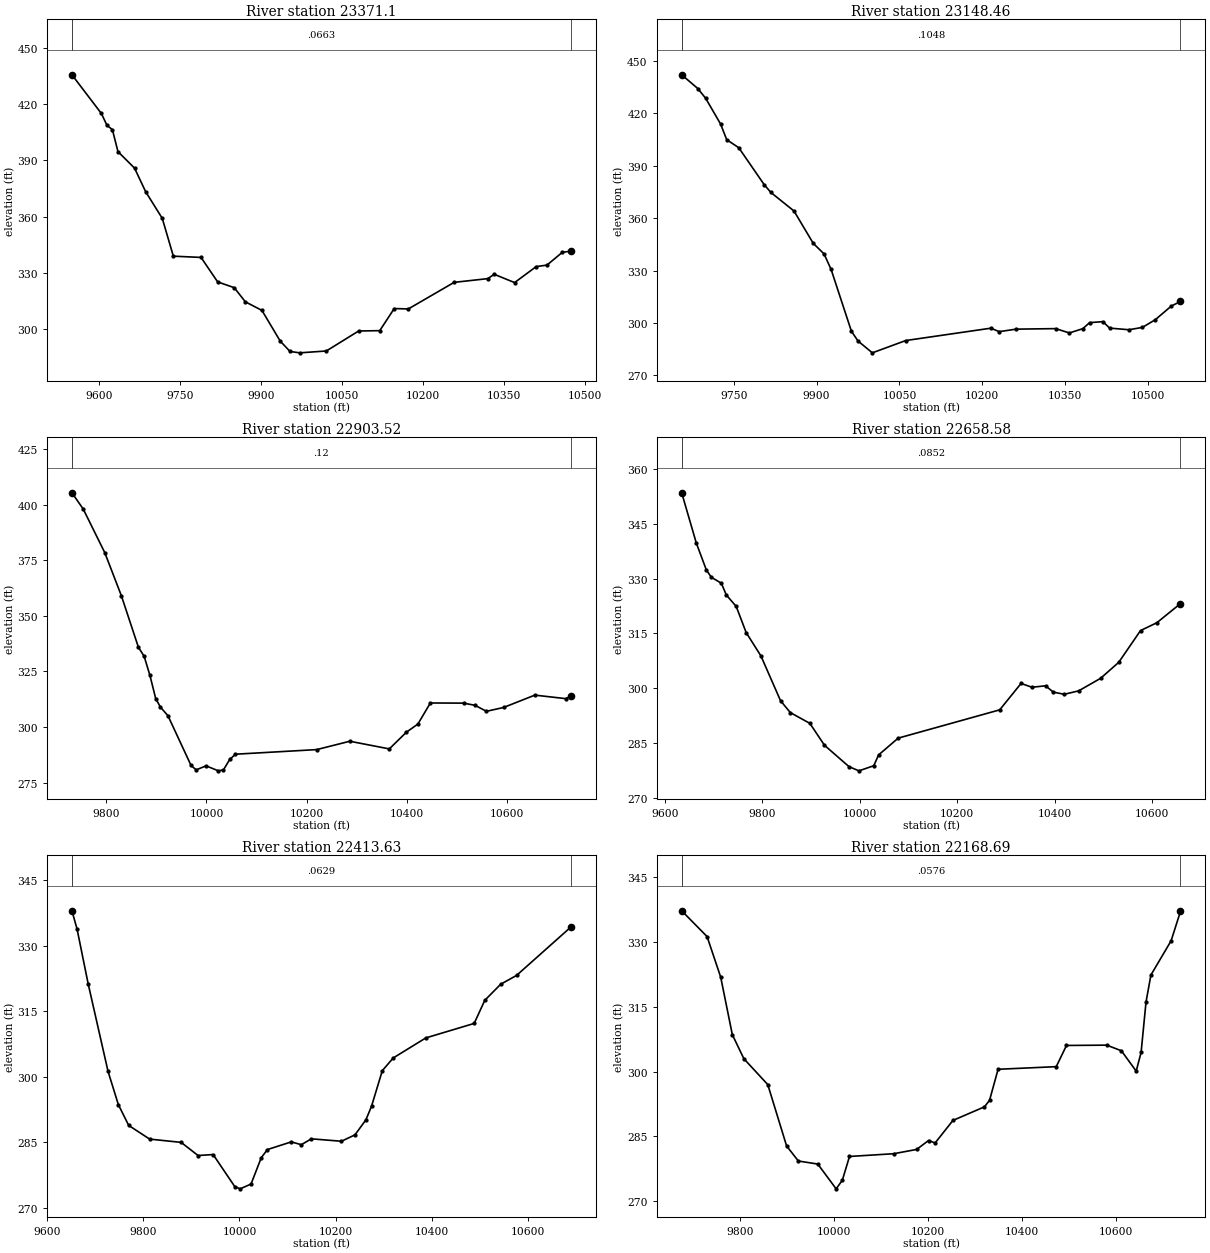
Type RM Length L Ch R = 1 , 23371.1,222.641100,222.641100,222.641100
XS GIS Cut Line= 6
899361.866527814 836817.92210045 899707.76100959836897.901632279
899869.018459001837004.237037308899974.066016196837092.249787025
900054.952849446837146.088056609900178.893106134837214.921246983
#Sta/Elev= 30
9549.074435.72919603.609415.08159613.873408.82229624.137406.3841  9634.4394.7025
9665.192 385.863 9685.72373.29339716.511359.05869737.039338.86519788.358338.2035
 9819.15325.13299849.941 322.0429870.469314.4999 9901.26309.90259935.154293.4942
9953.319287.98169971.484287.251210020.57288.246710080.46298.918210119.58299.0978
10146.35310.896910172.51310.696510257.46324.889310319.66326.870710331.67329.1886
10369.46324.761110409.47333.300810429.47334.101510457.87340.925410473.44341.5468
#Mann= 3 , 0 , 0
9549.074  0.0663       09549.074  0.0663       010473.44  0.0663       0
#XS Ineff= 2 , 0
       0                               0
Bank Sta=9549.074,10473.44
Exp/Cntr=0.3,0.1

Type RM Length L Ch R = 1 ,23148.46,244.942600,244.942600,244.942600
XS GIS Cut Line= 6
899326.358690346836858.805469156899471.601954371836914.632093281
899530.940642498836969.651198696899664.894892874837161.184217948
 899727.69266333837227.715080539900004.300251966837423.396688938
#Sta/Elev= 30
9655.767442.02289684.946434.15249699.215428.55069726.179 413.8489737.305404.8758
9759.122400.26149805.069379.17869817.279374.6675 9859.12364.06399893.902345.5847
9913.477339.5098 9926.23   330.7 9962.97295.33919974.984289.6514   10001282.8802
10061.41 289.91610215.56296.988510230.61295.013810261.44296.443410332.78296.7383
10357.75294.267910382.15296.724810394.29300.160910418.58300.743310430.56297.0327
 10465.5296.105710489.87297.430110513.21301.818710542.39309.677310558.88312.2745
#Mann= 3 , 0 , 0
9655.767  0.1048       09655.767  0.1048       010558.88  0.1048       0
#XS Ineff= 2 , 0
       0                10369.54       0
Bank Sta=9655.767,10558.88
Exp/Cntr=0.3,0.1

Type RM Length L Ch R = 1 ,22903.52,244.942600,244.942600,244.942600
XS GIS Cut Line= 6
899203.956456584837088.676786895899354.387288059837159.143758654
899400.141313519 837194.95940348899462.147661478837269.689782528
899679.962817596837361.806484411900063.633076921837567.198017827
#Sta/Elev= 30
9731.624 405.4139754.184398.08959797.136378.48529830.256359.09159864.245335.9016
9875.755331.78729887.265323.18849898.818312.74139908.271308.92479923.244 305.047
9969.295282.66849979.545280.70139999.218282.498810023.81280.255610033.94280.6837
10046.35285.366610057.95287.741910219.93289.814610285.97 293.57210364.78290.1296
10398.96297.664610421.75301.2996 10446.7310.801110512.93310.733610535.73309.7503
10558.52307.051510592.71308.770610655.13314.3351   10717312.747210726.66313.8917
#Mann= 3 , 0 , 0
9731.624    0.12       09731.624    0.12       010726.66    0.12       0
#XS Ineff= 2 , 0
       0                10407.57       0
Bank Sta=9731.624,10726.66
Exp/Cntr=0.3,0.1

Type RM Length L Ch R = 1 ,22658.58,244.942600,244.942600,244.942600
XS GIS Cut Line= 6
899075.780178493837416.584817389899272.539989742837453.752538823
899490.849416357837440.736732027899589.780122291837452.152497671
 899726.62615672837500.405998438900048.422204399837658.045848259
#Sta/Elev= 30
9634.886 353.5179664.938 339.7329685.508332.37679695.793330.38449716.229328.7556
9726.414325.54589746.784322.39039767.154315.2542 9797.43308.85969837.769296.5696
9857.806293.33399897.876290.38469927.894284.38289978.283278.52419998.552277.3879
10028.93278.784810038.96281.753510079.05286.341310287.38294.088310331.25 301.325
10353.34300.271710381.37300.669910397.56298.9313 10419.9298.346810449.34299.2851
10494.25302.711510531.59307.095510576.26315.785410609.77317.935810658.26323.1808
#Mann= 3 , 0 , 0
9634.886  0.0852       09634.886  0.0852       010658.26  0.0852       0
#XS Ineff= 2 , 0
       0                10267.57       0
Bank Sta=9634.886,10658.26
Exp/Cntr=0.3,0.1

Type RM Length L Ch R = 1 ,22413.63,244.942600,244.942600,244.942600
XS GIS Cut Line= 6
899035.014764431837532.655365436 899149.00766948837577.521885897
899313.245972304837652.648428145899663.403990894837842.164984217
899767.159078761837894.866671557899968.808985426837984.419669778
#Sta/Elev= 30
9651.277338.00589662.008333.81339684.983321.34269726.488301.23839747.982293.6258
9769.475288.87699813.047285.74419878.623284.99289913.863281.98849945.263282.2051
9990.178274.891810001.45274.358410024.16275.456310045.36 281.46410058.21 283.349
10107.99285.106710128.86284.462610149.74285.805510212.37285.250410240.48286.7104
10263.27290.1479   10275293.264110297.44301.411110320.23304.318610388.02 308.906
10488.66312.219510510.75317.505510543.89321.192210576.87323.205310689.64 334.248
#Mann= 3 , 0 , 0
9651.277  0.0629       09651.277  0.0629       010689.64  0.0629       0
#XS Ineff= 2 , 0
       0                10160.89       0
Bank Sta=9651.277,10689.64
Exp/Cntr=0.3,0.1

Type RM Length L Ch R = 1 ,22168.69,244.942600,244.942600,244.942600
XS GIS Cut Line= 6
898964.402429409837667.304837542899104.777768934 837762.09241846
899319.298100354837984.752003679899459.219516312838091.110702712
899595.038786045 838161.47308443899835.658158293838239.693611435
#Sta/Elev= 30
9675.658337.23939729.684331.26319758.694321.85959783.413308.5432 9807.99302.9634
9858.872296.96869898.945282.74529923.956279.26119965.276278.556410004.37272.8144
10017.54274.802710032.78280.315510126.81280.951110175.65281.942610201.02284.0142
10214.99283.446510252.96288.667810320.02291.816810330.83293.331610349.01300.5163
10472.79301.123710494.56306.035510580.14306.107310611.38304.806910642.91300.0925
10653.36304.4285 10663.8316.080410674.24322.357410717.26330.295710737.15337.1093
#Mann= 3 , 0 , 0
9675.658  0.0576       09675.658  0.0576       010737.15  0.0576       0
#XS Ineff= 2 , 0
       0                10176.39       0
Bank Sta=9675.658,10737.15
Exp/Cntr=0.3,0.1