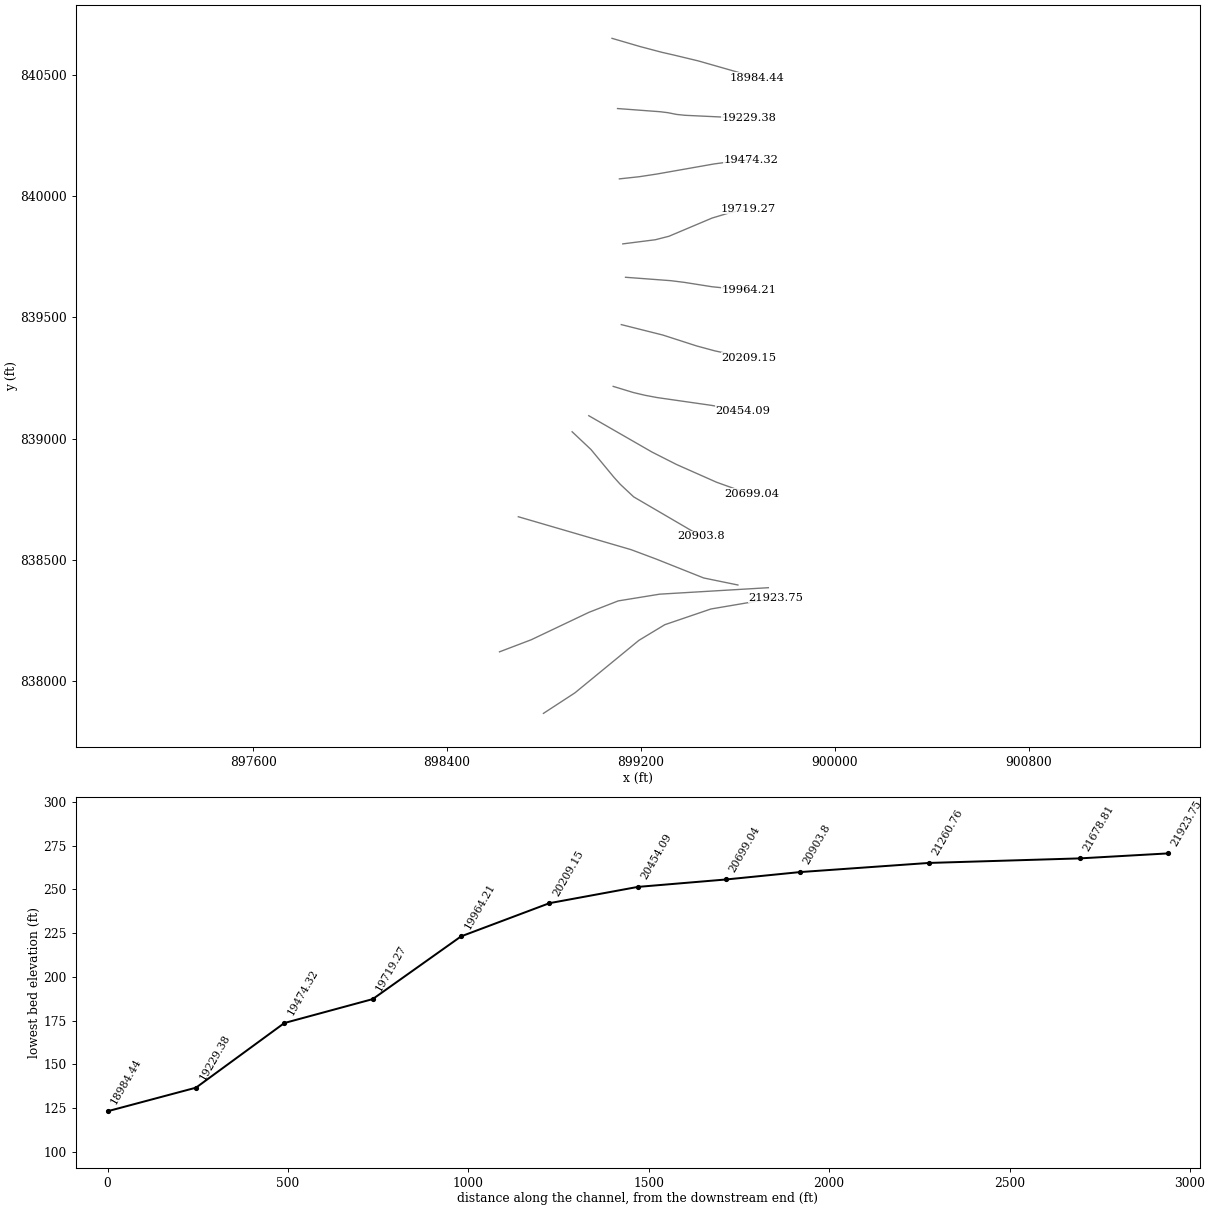
HEC-RAS study 16701_ras.prj: 16701

--- 16701_ras.g01 (geometry) --- (continued)

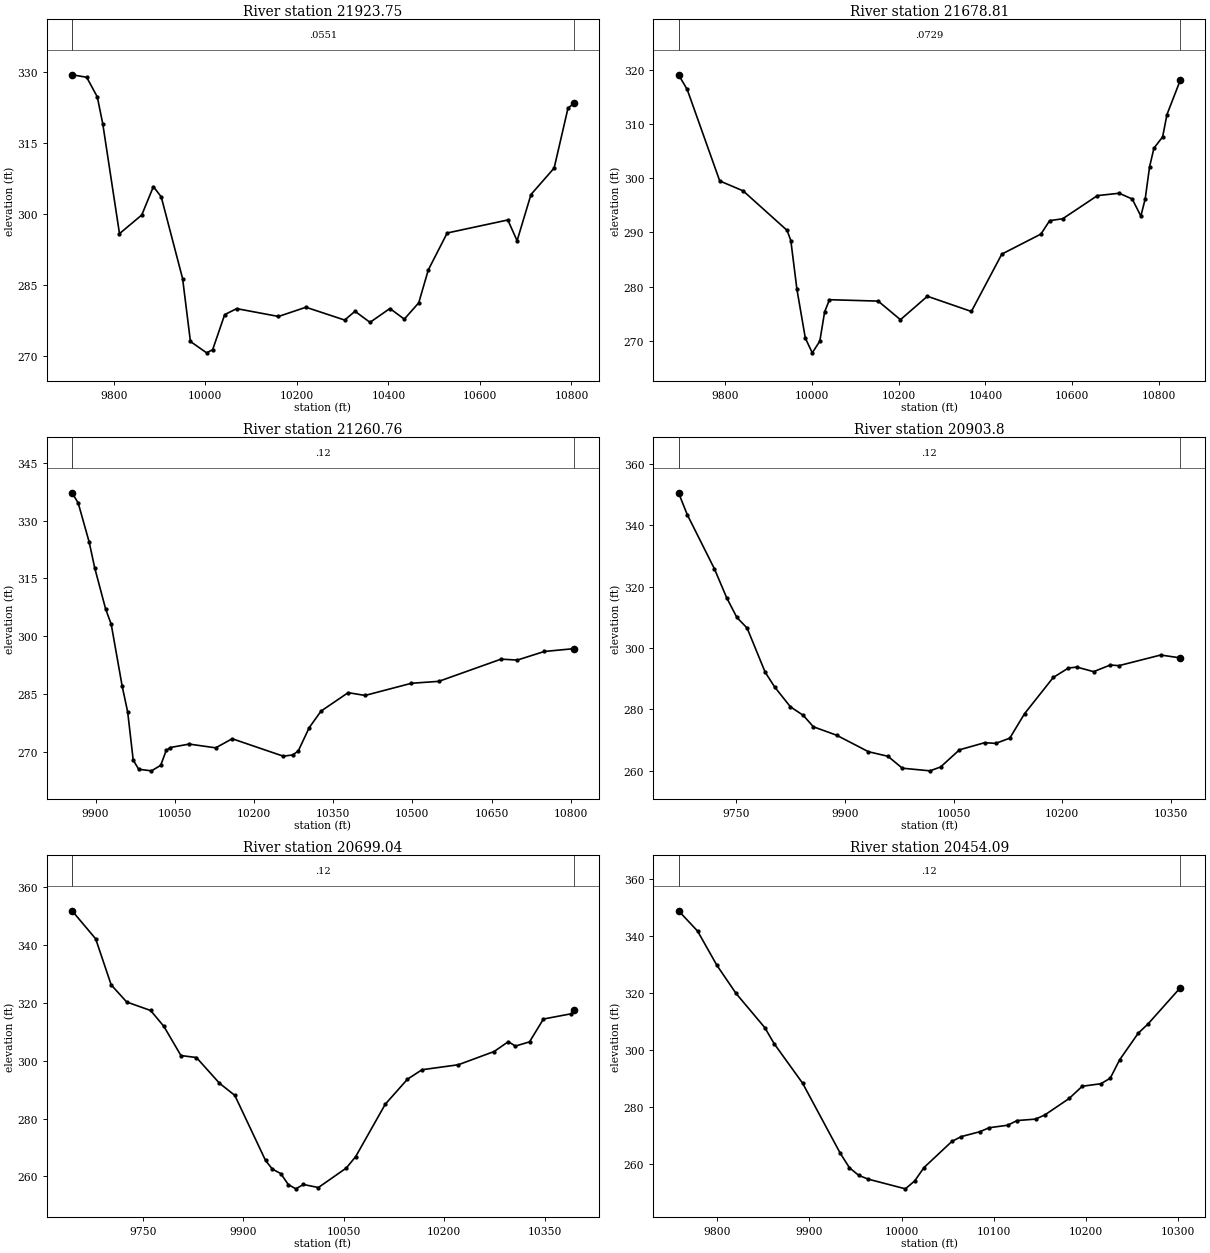
Type RM Length L Ch R = 1 ,21923.75,244.942600,244.942600,244.942600
XS GIS Cut Line= 6
898797.475408419 837865.69495142898927.399203136837950.376503617
 899191.38462122838167.023301017899298.305971109838231.615550296
899488.526743793838296.453482516899757.652242854838342.252991914
#Sta/Elev= 30
9709.048329.36379740.965328.83629764.156324.68979776.158318.97499812.655295.7949
9861.317299.73149886.707305.73419903.842303.56229950.543286.29129967.622273.0051
10003.02270.605310016.17271.268210042.47278.683810068.78279.9467   10160 278.291
   10220280.241310304.62 277.53310327.15279.387110359.95277.047410403.39279.9745
 10434.9277.730110466.41281.174510487.35288.147410528.59295.930210661.03298.6813
10681.27294.293910711.63304.062810762.23309.655910792.53322.3239 10805.3323.3169
#Mann= 3 , 0 , 0
9709.048  0.0551       09709.048  0.0551       0 10805.3  0.0551       0
#XS Ineff= 2 , 0
       0                10333.15       0
Bank Sta=9709.048,10805.3
Exp/Cntr=0.3,0.1

Type RM Length L Ch R = 1 ,21678.81,418.049900,418.049900,418.049900
XS GIS Cut Line= 6
898616.098799314838119.658969595898747.194499644838169.548235741
898985.153137173838282.653404022899105.899927265838329.813699588
899277.185199416838357.654169403899725.657935536 838384.31803569
#Sta/Elev= 30
9692.751319.10529712.672316.40019787.703299.49969841.618297.66889942.955290.3696
 9951.58288.48199965.687279.46279984.986270.4804   10001267.753510018.42269.9139
10029.55275.344110040.69277.567210152.96277.306810204.23273.873610266.38278.2012
10367.75275.394110437.97285.9917 10528.1289.689710548.13292.161610578.18292.5122
10658.29296.791210708.37297.224810738.41296.170310758.44293.015110768.47296.2015
 10778.5302.106610788.53305.5447 10808.6  307.6410818.63311.769210849.39318.1251
#Mann= 3 , 0 , 0
9692.751  0.0729       09692.751  0.0729       010849.39  0.0729       0
#XS Ineff= 2 , 0
       0                10424.48       0
Bank Sta=9692.751,10849.39
Exp/Cntr=0.3,0.1

Type RM Length L Ch R = 1 ,21260.76,356.960500,356.960500,356.960500
XS GIS Cut Line= 5
898693.851462795838677.147035872899159.256431882838541.285435585
899263.262986552838502.357515793899458.912645891838424.454746554
899599.973415418838395.500788706
#Sta/Elev= 30
9855.482337.21039867.096334.55889887.931324.40529898.348317.75919919.183307.0296
  9929.6303.16439950.435287.05599960.852280.3803 9971.27267.95179981.687265.5606
10005.89265.153110023.36266.580210033.77270.431510041.57271.197910077.26272.0884
10127.53271.113510158.78273.469510255.69 268.94610273.37269.276110283.79270.2643
10304.63276.337210327.06280.634710378.48285.414810410.51284.691510498.29287.8451
10550.11288.343410668.17294.104310698.79293.853710749.84296.079510805.96296.8158
#Mann= 3 , 0 , 0
9855.482    0.12       09855.482    0.12       010805.96    0.12       0
#XS Ineff= 2 , 0
       0                10433.24       0
Bank Sta=9855.482,10805.96
Exp/Cntr=0.3,0.1

Type RM Length L Ch R = 1 , 20903.8,204.760100,204.760100,204.760100
XS GIS Cut Line= 6
898915.903289447839027.847640485898993.696628844838954.523111856
899088.686055028838839.651614439899114.331870563838811.215511997
899169.781238337838759.231201923899448.362467411838596.465507722
#Sta/Elev= 30
9670.036350.66689682.051343.54119719.628 325.8379736.512316.41279750.622309.9762
9764.732306.52539789.647292.12669802.925287.24849824.587280.81699842.304278.0348
 9856.29274.30049888.245271.56619932.355266.16859959.287264.67689979.065260.7917
10017.28259.929210031.94261.187910058.02266.794310092.76269.107910108.25268.8971
10127.51270.593910147.89278.573810187.54290.395610208.58293.489810220.16293.7829
10243.32292.297310266.49294.476510278.07294.242810335.98297.724510363.04296.7848
#Mann= 3 , 0 , 0
9670.036    0.12       09670.036    0.12       010363.04    0.12       0
#XS Ineff= 2 , 0
       0                10223.18       0
Bank Sta=9670.036,10363.04
Exp/Cntr=0.3,0.1

Type RM Length L Ch R = 1 ,20699.04,244.942600,244.942600,244.942600
XS GIS Cut Line= 6
898984.545016474839094.131511506899245.513302792838944.110891492
899346.663303485838892.810626545899512.406789634838819.365995689
899586.846124935838792.780475278899658.653978602838772.086317238
#Sta/Elev= 30
9644.036351.75539679.295342.0611 9702.45326.16449725.605320.25179761.377317.3116
9781.221311.81599806.647301.75069829.802301.06459864.206292.1867 9887.14287.9875
9933.007265.51859943.245262.52259955.756 260.9839967.028257.1776  9978.3255.7077
9989.573257.209510011.99256.161510053.55262.872210067.69266.843110111.89284.9427
10145.03293.578210166.78296.847310220.95298.565610274.42303.134610295.66306.5328
10306.28305.019810327.34 306.47810348.16314.365310389.79316.185610393.59 317.428
#Mann= 3 , 0 , 0
9644.036    0.12       09644.036    0.12       010393.59    0.12       0
#XS Ineff= 2 , 0
       0                               0
Bank Sta=9644.036,10393.59
Exp/Cntr=0.3,0.1

Type RM Length L Ch R = 1 ,20454.09,244.942600,244.942600,244.942600
XS GIS Cut Line= 6
899085.416532176839215.082761231899168.781125815839189.694446176
899216.256879449839178.490051296899266.541115566839169.006649179
899487.076327055839137.359903464899619.958869526839114.848838826
#Sta/Elev= 30
9757.945348.97449778.586341.87089799.591329.84569820.385319.9815  9851.5308.0239
9861.775 302.3529892.599288.51519933.316 264.0349943.493258.83129953.616256.1675
 9963.73254.863210004.17251.452810014.27254.221310024.37258.914110054.67268.0847
10064.77269.766310084.97271.482410095.07272.878410115.26 273.76710125.36275.3991
10145.56275.911310155.66277.391610181.99 283.15210196.18287.433210216.46288.3222
10226.61290.266310236.75296.706610257.03 306.07910267.18309.142910302.63321.9854
#Mann= 3 , 0 , 0
9757.945    0.12       09757.945    0.12       010302.63    0.12       0
#XS Ineff= 2 , 0
       0                               0
Bank Sta=9757.945,10302.63
Exp/Cntr=0.3,0.1

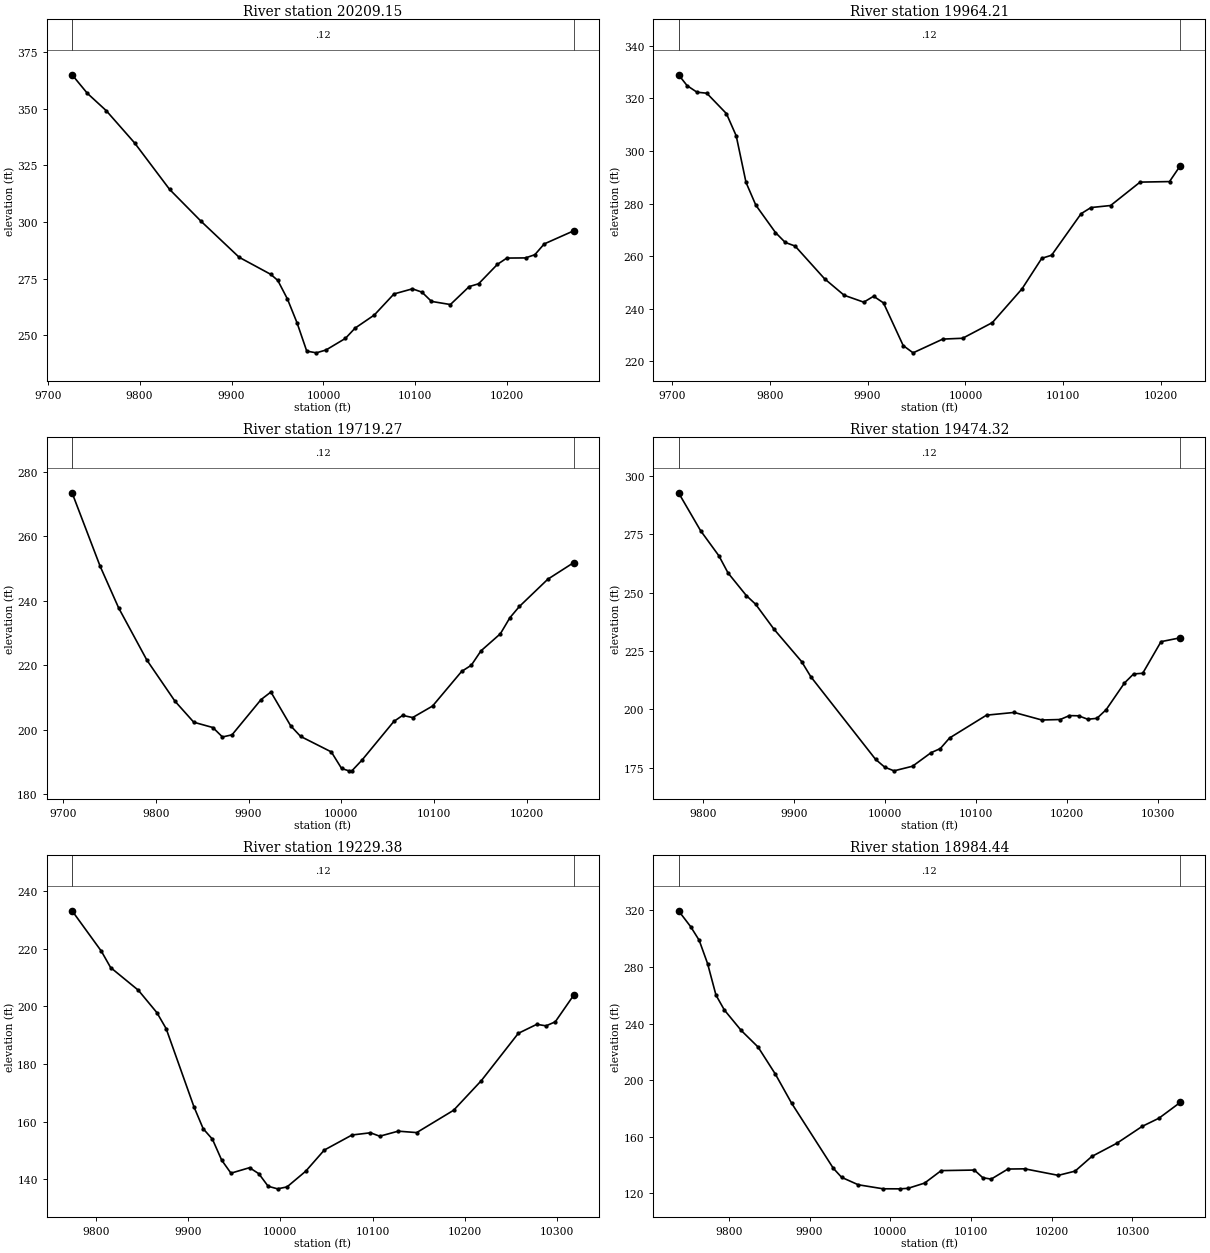
Type RM Length L Ch R = 1 ,20209.15,244.942600,244.942600,244.942600
XS GIS Cut Line= 6
 899118.78866184839470.058992277899290.339107557839426.952355028
899429.847205777839381.968508813899505.031161525 839361.64272329
899579.752382667839345.524545096899646.780161942839333.618055764
#Sta/Elev= 30
 9726.55365.08259743.192356.87659763.722349.2186 9794.52334.98419832.606314.4313
9866.908300.30519908.346284.39279942.687276.85779950.342274.17469960.841265.9537
 9971.34 255.3779981.839242.91999992.338242.154610002.85 243.42410023.89248.5361
10034.42253.078810055.37258.883510076.74268.188810096.81270.450310107.17268.9868
10117.53264.893810138.12263.506910158.58271.448110168.81272.687510189.27281.2735
 10199.5284.050810219.84284.1224   10230285.542510240.16290.298610272.43296.1308
#Mann= 3 , 0 , 0
 9726.55    0.12       0 9726.55    0.12       010272.43    0.12       0
#XS Ineff= 2 , 0
       0                               0
Bank Sta=9726.55,10272.43
Exp/Cntr=0.3,0.1

Type RM Length L Ch R = 1 ,19964.21,244.942600,244.942600,244.942600
XS GIS Cut Line= 6
899136.227266595839665.398943705899322.763619435839651.382558911
899378.406106404839644.440366273899493.121568242839626.342015595
899591.986232612839616.205341962899646.028875286839612.691168901
#Sta/Elev= 30
9706.828329.01699715.626324.87489725.654322.39359735.682321.99979755.739314.2525
9765.767305.79039775.795288.04539785.823279.38359805.879268.97329815.908265.1892
9825.936263.8289 9856.02251.38279876.077245.08919896.144242.46019906.222 244.721
9916.299242.17069936.454225.92469946.532223.17239976.909228.40549997.173228.7225
10027.53234.682710057.88247.543610078.04259.153310088.09 260.32910118.25276.1429
 10128.3278.472110148.41279.252710178.52288.160410208.59288.361910219.64294.4309
#Mann= 3 , 0 , 0
9706.828    0.12       09706.828    0.12       010219.64    0.12       0
#XS Ineff= 2 , 0
       0                               0
Bank Sta=9706.828,10219.64
Exp/Cntr=0.3,0.1

Type RM Length L Ch R = 1 ,19719.27,244.942600,244.942600,244.942600
XS GIS Cut Line= 6
899124.941901164839803.195171483899259.090602812839820.264610063
899315.595332524839834.698202092899493.306298257839909.731178618
899563.869305925839931.028110413 899642.42016827839947.946852012
#Sta/Elev= 30
9709.835273.49889740.011250.77779760.089237.77479790.355221.67879820.748 208.894
9841.009202.37859861.574200.73229871.895197.80779882.216198.47699913.478209.3958
9924.117211.74039945.394201.27759956.094197.99049989.224 193.17610000.29188.0435
10008.14187.311710011.39187.318810022.48190.706910056.59202.616810066.09204.4985
10076.85203.826310098.31207.392410129.65218.123210140.09220.049710150.54 224.517
 10171.4229.794810181.64234.762510191.87 238.25210222.57246.7182 10250.6 251.886
#Mann= 3 , 0 , 0
9709.835    0.12       09709.835    0.12       0 10250.6    0.12       0
#XS Ineff= 2 , 0
       0                               0
Bank Sta=9709.835,10250.6
Exp/Cntr=0.3,0.1

Type RM Length L Ch R = 1 ,19474.32,244.942600,244.942600,244.942600
XS GIS Cut Line= 6
899110.904812085840071.495903691  899192.6002923840080.343431033
899265.648396527840091.482092198899502.629474896840133.268222275
899580.202574567840143.588740609899656.107057594840150.935540262
#Sta/Elev= 30
 9772.91 292.8119797.145 276.5649817.263265.78729827.321258.42919847.438248.7278
9857.511245.07919877.742234.35369908.089 220.4769918.204213.97639989.291178.5858
9999.453175.185710009.62173.627510029.96175.6033 10050.3   181.410060.47183.1712
10070.64187.709510111.23 197.49210141.63198.661710172.01195.416310192.19195.6258
10202.28197.308310212.37197.214210222.46195.734110232.54196.132810242.63199.8221
10262.75211.264610272.79215.149810282.84215.454110302.93228.995610324.14230.6583
#Mann= 3 , 0 , 0
 9772.91    0.12       0 9772.91    0.12       010324.14    0.12       0
#XS Ineff= 2 , 0
       0                               0
Bank Sta=9772.91,10324.14
Exp/Cntr=0.3,0.1

Type RM Length L Ch R = 1 ,19229.38,244.942600,244.942600,244.942600
XS GIS Cut Line= 6
899103.347766248840361.708231871899278.440103465840348.637593079
899311.515252885840344.558723946899347.320349703840337.397940816
899382.165831748840333.815560234899645.066435804840321.425947146
#Sta/Elev= 30
9774.475233.24289806.215219.20319816.243213.52479846.326205.63069866.382197.8637
 9876.41192.30739906.493165.19199916.521157.55619926.549153.90639936.577 146.638
9946.605142.1111 9966.74144.01399976.815141.92489986.936137.55919997.142136.6718
10007.35137.337910027.62142.793610047.72150.133910077.78155.3742 10097.8156.1403
10107.81154.947610127.83156.703410147.85 156.20710187.89163.969810217.92174.2643
10257.96 190.68510277.98193.808610287.99193.2791   10298194.682310318.13204.0072
#Mann= 3 , 0 , 0
9774.475    0.12       09774.475    0.12       010318.13    0.12       0
#XS Ineff= 2 , 0
       0                10081.17       0
Bank Sta=9774.475,10318.13
Exp/Cntr=0.3,0.1

Type RM Length L Ch R = 1 ,18984.44,244.942600,244.942600,244.942600
XS GIS Cut Line= 6
899080.471376743840651.457656526899195.607478715840617.727758358
899285.873803825840593.875220344899334.678155029 840582.73908884
899436.876547463840558.208152045899680.409473347840488.659118726
#Sta/Elev= 30
9737.601319.7591 9752.74308.4466 9763.16298.93129773.581282.44469784.001 260.128
9794.421249.59259815.262235.15989836.102223.47829857.576204.30189877.634183.8142
 9929.35 137.7659939.694131.33129960.304 126.0819991.082123.237610011.62123.2056
 10021.9123.558210042.47127.266210063.04136.087110104.17136.481910114.55131.0951
10124.95130.072610145.75137.199910166.55137.354910208.15132.739310228.95135.7193
10249.75146.111610280.95155.511710312.15167.370310332.95173.157610359.37 184.345
#Mann= 3 , 0 , 0
9737.601    0.12       09737.601    0.12       010359.37    0.12       0
#XS Ineff= 2 , 0
       0                10158.99       0
Bank Sta=9737.601,10359.37
Exp/Cntr=0.3,0.1