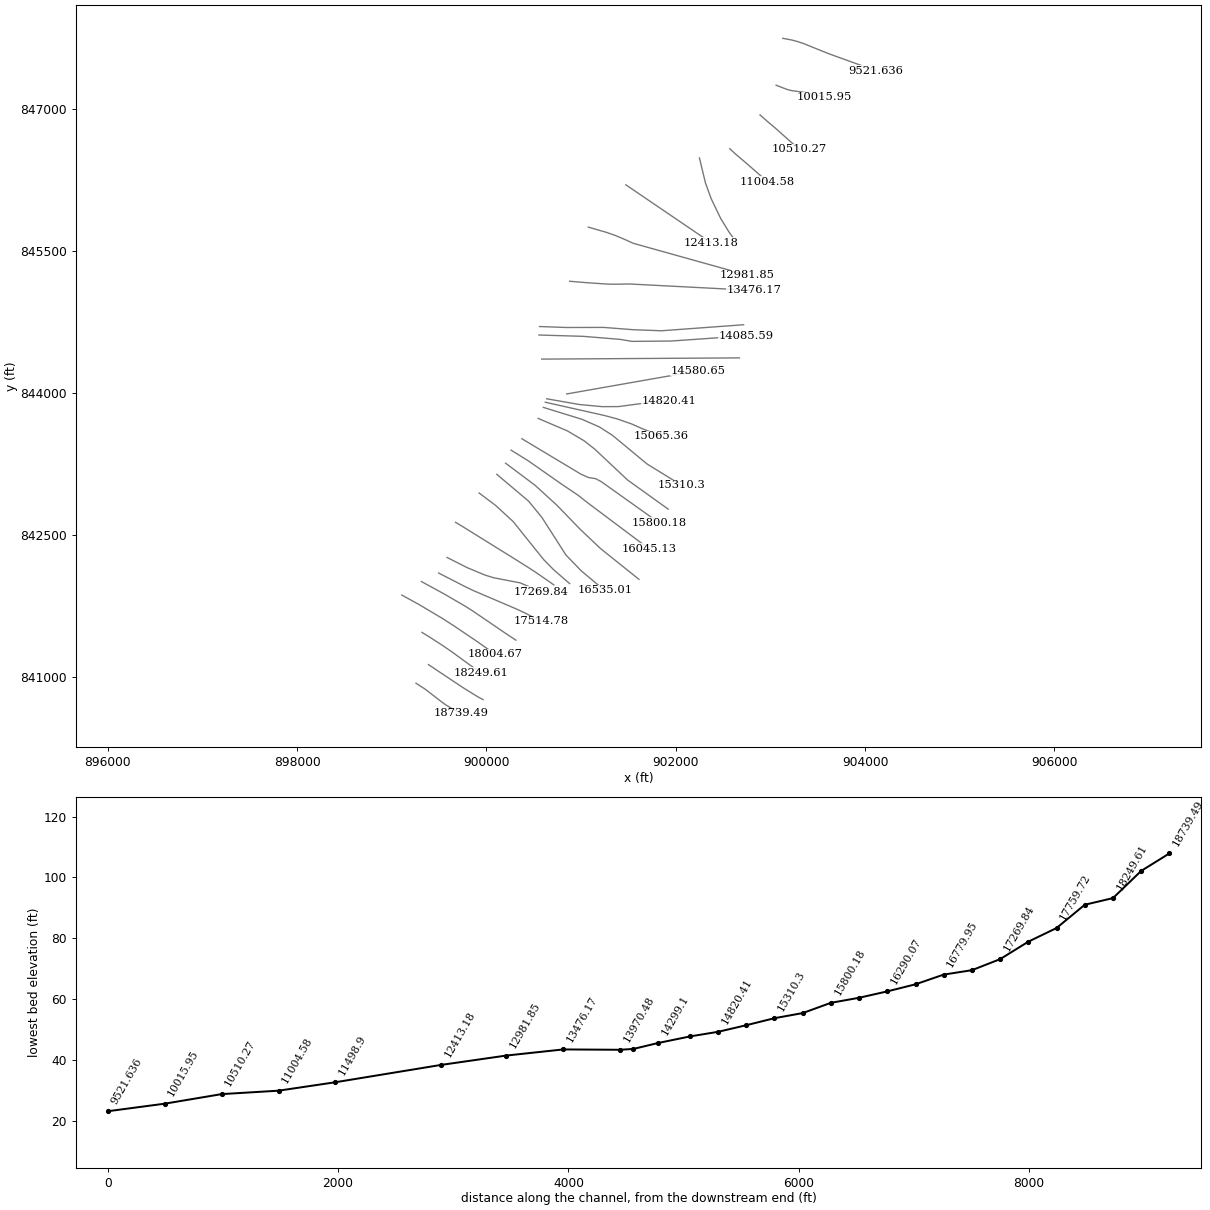
HEC-RAS study 16701_ras.prj: 16701

--- 16701_ras.g01 (geometry) --- (continued)

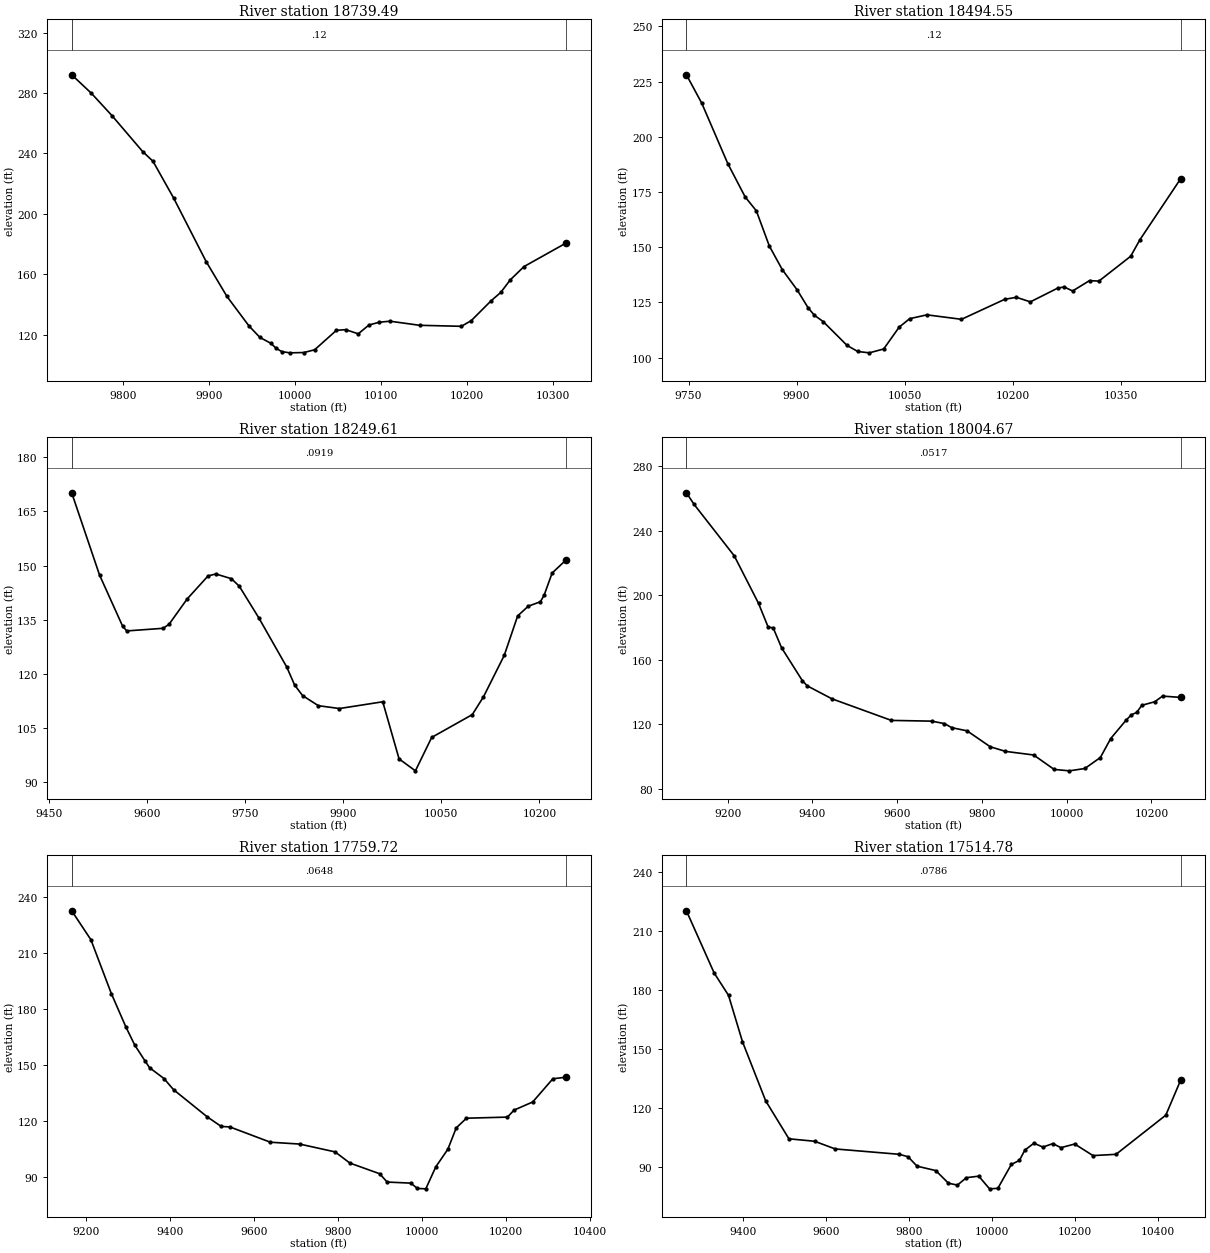
Type RM Length L Ch R = 1 ,18739.49,244.942700,244.942700,244.942700
XS GIS Cut Line= 6
899255.455560361840932.222051302899349.962012495840871.150147688
899529.995036975840732.122277453 899569.25208764840704.138607326
899653.161788202840653.320415196899733.051661821840613.533394164
#Sta/Elev= 30
 9739.94292.05539762.912279.78799786.808 265.0319822.651 241.1679834.598234.7807
9858.726210.34639896.646168.20269920.767145.23039946.339125.75249959.125118.0984
 9971.91114.19359978.089110.85719984.696108.67619994.137107.888710010.37108.0882
10022.85109.906210048.24122.804410059.07123.238610073.63120.481710086.12126.3248
 10098.4128.198210110.68128.835610145.07126.131210193.78125.456710205.33129.2543
10228.37142.363410239.59 147.87610250.81156.292210266.69165.022510315.57180.5778
#Mann= 3 , 0 , 0
 9739.94    0.12       0 9739.94    0.12       010315.57    0.12       0
#XS Ineff= 2 , 0
       0                10108.73       0
Bank Sta=9739.94,10315.57
Exp/Cntr=0.3,0.1

Type RM Length L Ch R = 1 ,18494.55,244.942600,244.942600,244.942600
XS GIS Cut Line= 6
 899387.06947356841128.734713031899395.041712645841123.723423862
899596.667492309840988.986885871899769.037237401 840874.66046788
899903.644704869840791.867768993899964.493669193840758.351429033
#Sta/Elev= 30
9747.082228.10329768.476215.16339804.558187.83459828.612172.78539844.192166.4614
 9862.19150.53679880.188 139.8289900.776130.67559916.185122.47499924.831119.1443
9936.858116.33159970.179105.48419984.967102.7576   10001102.140610020.99103.8911
10042.41113.761510056.99117.603410080.99119.354110128.99117.328810188.99126.3858
10205.22127.303410224.58125.232410262.45131.437810271.54131.986510283.28130.1649
10306.76134.858210319.72134.623910363.87145.885810376.83153.436710433.34181.0428
#Mann= 3 , 0 , 0
9747.082    0.12       09747.082    0.12       010433.34    0.12       0
#XS Ineff= 2 , 0
       0                10119.79       0
Bank Sta=9747.082,10433.34
Exp/Cntr=0.3,0.1

Type RM Length L Ch R = 1 ,18249.61,244.942600,244.942600,244.942600
XS GIS Cut Line= 6
899318.725519099841469.084849784 899402.54190089841417.543705969
899528.656510704841335.925910975899632.974359409841265.149915955
899817.136017031841130.351840288  899942.8183776841043.321183625
#Sta/Elev= 30
9484.956170.1315 9527.54147.37269562.759133.26019569.117131.91669624.845132.6426
9633.926133.77969661.655140.79339693.483147.13129705.395147.67199729.217146.3562
9741.239144.27549770.845 135.5969813.745121.94429825.829116.94899837.913  114.05
9862.121111.23379894.361110.44879960.593112.31439985.54496.5121810010.5293.21241
10035.42102.460310097.48 108.764 10114.6113.688910146.33125.138610166.85136.0609
10182.98 138.74610201.68139.988610207.38141.829710219.61147.936710240.75151.5294
#Mann= 3 , 0 , 0
9484.956  0.0919       09484.956  0.0919       010240.75  0.0919       0
#XS Ineff= 2 , 0
       0                               0
Bank Sta=9484.956,10240.75
Exp/Cntr=0.3,0.1

Type RM Length L Ch R = 1 ,18004.67,244.942600,244.942600,244.942600
XS GIS Cut Line= 6
899105.746657502841863.425592322899284.172400408841765.561032087
 899536.63875712841615.505763008899663.533316627841533.512620491
899887.756329787841381.966787279900090.213277894841240.037600727
#Sta/Elev= 30
9102.855263.62579120.727256.50289215.789224.4613 9272.99194.9892 9295.87180.1502
 9307.48179.82039327.381167.42159376.718146.86519388.284143.72949446.115135.7398
9586.432122.32749681.466121.87779711.562120.35499729.089117.80369765.013 115.852
9819.731105.96989855.343103.11679922.131100.85799970.47591.8976510006.5991.02438
10042.8792.4767110079.5599.30057   10104111.097510140.67122.6236 10152.9125.8256
10165.12127.256410177.35131.701510207.76 133.90610226.25137.414210269.05136.6032
#Mann= 3 , 0 , 0
9102.855  0.0517       09102.855  0.0517       010269.05  0.0517       0
#XS Ineff= 2 , 0
       0                               0
Bank Sta=9102.855,10269.05
Exp/Cntr=0.3,0.1

Type RM Length L Ch R = 1 ,17759.72,244.942600,244.942600,244.942600
XS GIS Cut Line= 6
899312.178688847842006.891368119899549.184314786841877.539338826
899777.536385454841744.933286233899857.121006855841694.354718768
900196.334543534841462.955041664900311.362587575841387.096046342
#Sta/Elev= 30
9165.789232.74889211.484217.21789260.142188.27839294.979170.26099315.853160.6287
9339.889152.25719351.282148.42869385.459142.63729408.244136.6565 9488.48122.0527
9521.955116.88449542.209116.65569638.771108.42699708.714 107.4329792.964103.2238
9827.966 97.24089899.15791.482049916.84587.025929973.173 86.45359988.83383.61204
10008.8683.3835610032.6795.2037210061.35104.6324 10081.3116.115310105.68121.3292
 10203.2121.916810219.12125.689610263.41130.041910311.37142.502910342.62143.3511
#Mann= 3 , 0 , 0
9165.789  0.0648       09165.789  0.0648       010342.62  0.0648       0
#XS Ineff= 2 , 0
       0                               0
Bank Sta=9165.789,10342.62
Exp/Cntr=0.3,0.1

Type RM Length L Ch R = 1 ,17514.78,244.942600,244.942600,244.942600
XS GIS Cut Line= 6
 899495.07745353842096.165158725899779.060283727841950.500914186
899865.861833457841909.196463254900318.207771913841715.743602276
900411.663256652841672.059181688900573.250492354841587.976845735
#Sta/Elev= 30
9262.677220.13519329.631188.52659364.254177.19149397.892153.65739453.955123.5885
9510.018104.3174  9571.9103.07059621.64899.167639775.70196.453159797.37495.22966
9819.04890.426639864.29388.175879894.90681.767449916.57980.796999938.25384.58085
9968.10185.338649994.05378.9032410014.1479.1567810046.6791.3043310066.1693.35443
10079.2798.5588910101.07102.072210122.88100.110910146.73101.873410166.4899.81954
10199.55101.667410243.7195.7859610299.2696.4350510419.36116.316110455.31134.1648
#Mann= 3 , 0 , 0
9262.677  0.0786       09262.677  0.0786       010455.31  0.0786       0
#XS Ineff= 2 , 0
       0                               0
Bank Sta=9262.677,10455.31
Exp/Cntr=0.3,0.1

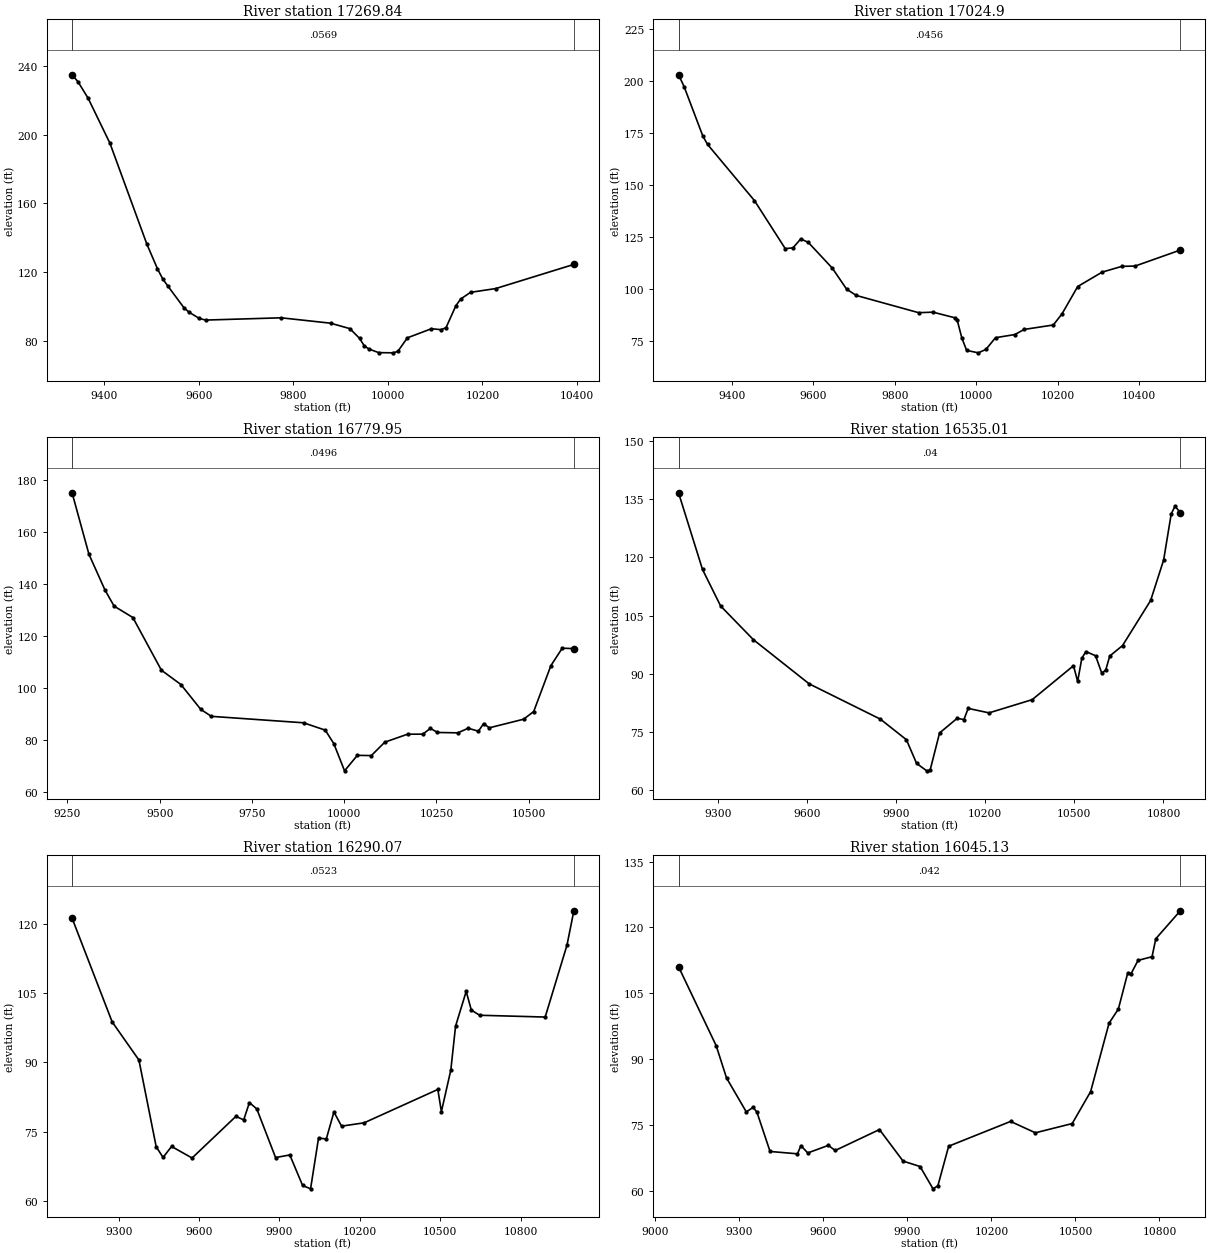
Type RM Length L Ch R = 1 ,17269.84,244.942600,244.942600,244.942600
XS GIS Cut Line= 6
899584.239353968842260.895504511899794.541295752842154.130349594
899985.793100682842074.300201399900078.728286415842045.986044674
900356.007590388841992.354246618900575.304881537 841899.68634394
#Sta/Elev= 30
9331.848 234.791 9344.45230.70399365.827221.15339411.909195.03249490.212136.2565
9512.504122.0378 9523.65116.11039534.796111.87919568.22699.476279579.18296.82522
9601.09493.138469614.55192.216399774.18693.533129878.62790.407829919.54687.23209
9940.005 81.58429950.17377.16815 9960.2875.337169980.49473.2946410010.8273.16877
10020.9373.9839710041.1681.8924910092.0787.1819510112.65 86.638310122.9487.80312
10143.65100.473410153.82104.426910174.82108.339710227.73110.510910393.36124.5681
#Mann= 3 , 0 , 0
9331.848  0.0569       09331.848  0.0569       010393.36  0.0569       0
#XS Ineff= 2 , 0
       0                               0
Bank Sta=9331.848,10393.36
Exp/Cntr=0.3,0.1

Type RM Length L Ch R = 1 , 17024.9,244.942600,244.942600,244.942600
XS GIS Cut Line= 6
899673.792862404842631.988195723899743.378607678 842590.48899765
900293.939681706842248.321099525900453.202990195842148.017241192
900548.142413394842085.479477827900712.245095457841970.972643727
#Sta/Elev= 30
9269.754203.09639283.397197.41919329.376173.66119341.019169.62449455.896 142.698
9531.675 119.575 9550.62119.97799569.564124.24719588.162122.57949647.031  110.23
9682.353 100.0829705.901 97.09839858.96288.819089894.28389.070339948.458 86.3385
9953.15385.536159964.92776.655669976.70170.7107310005.2569.5350610024.0171.18038
10047.5276.8065910094.7978.3085910117.8380.7745910189.3782.9152810210.8888.31299
10249.24 101.39310309.22108.311910357.73111.079910390.13111.222110501.01118.9123
#Mann= 3 , 0 , 0
9269.754  0.0456       09269.754  0.0456       010501.01  0.0456       0
#XS Ineff= 2 , 0
       0                               0
Bank Sta=9269.754,10501.01
Exp/Cntr=0.3,0.1

Type RM Length L Ch R = 1 ,16779.95,244.942600,244.942600,244.942600
XS GIS Cut Line= 6
899922.743092035842941.690807243 900096.11233441842811.309030022
900282.151127252842640.348261898900604.916692995842237.869791986
900710.570589906842130.691322523900879.101873922841984.944394243
#Sta/Elev= 30
9262.799174.99359308.476151.36679351.839137.64319376.666131.42389427.511127.0262
9504.751106.79059557.656101.27429611.46791.721819640.07489.043949889.83686.56488
9948.72583.737299971.87978.56447   1000168.0917310035.6574.0510210073.5173.95428
10110.0979.1172610171.6882.1771610213.26 82.191210233.5184.4330510252.7982.84572
10307.9582.69452 10335.984.4728210363.7583.3188910377.6886.2646410393.1884.63247
10486.1687.9429610513.41 90.8967   10560108.541110590.72115.247410622.22115.0778
#Mann= 3 , 0 , 0
9262.799  0.0496       09262.799  0.0496       010622.22  0.0496       0
#XS Ineff= 2 , 0
       0                               0
Bank Sta=9262.799,10622.22
Exp/Cntr=0.3,0.1

Type RM Length L Ch R = 1 ,16535.01,244.942600,244.942600,244.942600
XS GIS Cut Line= 6
900109.239867002843139.431987568900445.222907499842856.079936026
900585.983012494 842683.63613929900839.574690571 842287.60032185
 901000.04096925842121.078107595 901248.98235886841912.677648508
#Sta/Elev= 30
9166.736136.71339247.517116.89949308.579107.47029418.99698.763759606.65887.37138
9846.56678.253469934.29772.937729968.57766.8248410002.7964.9002710014.1765.07381
   1004674.6839710104.8878.4387810128.1878.1559210142.34 81.031110212.5579.86938
10358.1183.28828 10497.192.0483110511.1387.9924710525.1693.9688510538.8795.71467
10571.4394.6244210592.4590.1118910605.8490.9555710619.2494.55395 10662.297.24309
10756.94108.894410800.76  119.3510826.33131.261810839.12133.242110856.98131.5936
#Mann= 3 , 0 , 0
9166.736    0.04       09166.736    0.04       010856.98    0.04       0
#XS Ineff= 2 , 0
       0                               0
Bank Sta=9166.736,10856.98
Exp/Cntr=0.3,0.1

Type RM Length L Ch R = 1 ,16290.07,244.942600,244.942600,244.942600
XS GIS Cut Line= 6
900202.254744665843256.924652235900516.051678895843021.585109441
900745.407186575842811.624679361900992.548601115 842556.39965497
901205.352586281842355.044101155901611.190112392842030.034396707
#Sta/Elev= 30
9126.259121.23729275.70998.76595 9375.6990.488159440.09571.701179465.72569.37995
9497.455  71.7649573.958 69.25959737.46978.284439766.58377.520489787.88381.27349
9815.40479.893499885.46469.358139938.58869.920879986.24563.3187210016.02 62.5794
10045.7773.5933410074.6973.3772310103.12 79.231310131.6176.1660210215.7876.88535
10490.8384.1150710504.0579.3009310539.2988.3420910556.9397.83507 10596.6105.3645
10615.72101.319610646.68100.194310891.2699.8042510972.58115.379910998.26122.8333
#Mann= 3 , 0 , 0
9126.259  0.0523       09126.259  0.0523       010998.26  0.0523       0
#XS Ineff= 2 , 0
       09794.446                       0
Bank Sta=9126.259,10998.26
Exp/Cntr=0.3,0.1

Type RM Length L Ch R = 1 ,16045.13,244.942600,244.942600,244.942600
XS GIS Cut Line= 6
900260.043369612843394.962552985900442.445399942 843281.64313402
 900793.60047362 843035.92084935900965.728907803 842920.27780254
 901060.75961439842845.224387644901716.535735173842353.502665877
#Sta/Elev= 30
9082.996111.04319217.28593.086849254.411 85.71659325.05577.981419349.25279.03365
9362.86877.937289409.74568.985599507.63668.448839519.88370.306449544.37768.64949
 9617.8670.369939642.35569.205189800.34173.975599884.67266.790919945.28865.56112
 9991.6460.4760310008.9661.1824410047.4770.18112 10268.575.8226610357.0973.23463
10488.5575.3407510554.2882.61051   1062098.1762410653.36101.412710686.79109.6246
 10698.7109.465110723.66112.488610773.58113.328310787.08117.422710874.56123.7839
#Mann= 3 , 0 , 0
9082.996   0.042       09082.996   0.042       010874.56   0.042       0
#XS Ineff= 2 , 0
       09782.023                       0
Bank Sta=9082.996,10874.56
Exp/Cntr=0.3,0.1

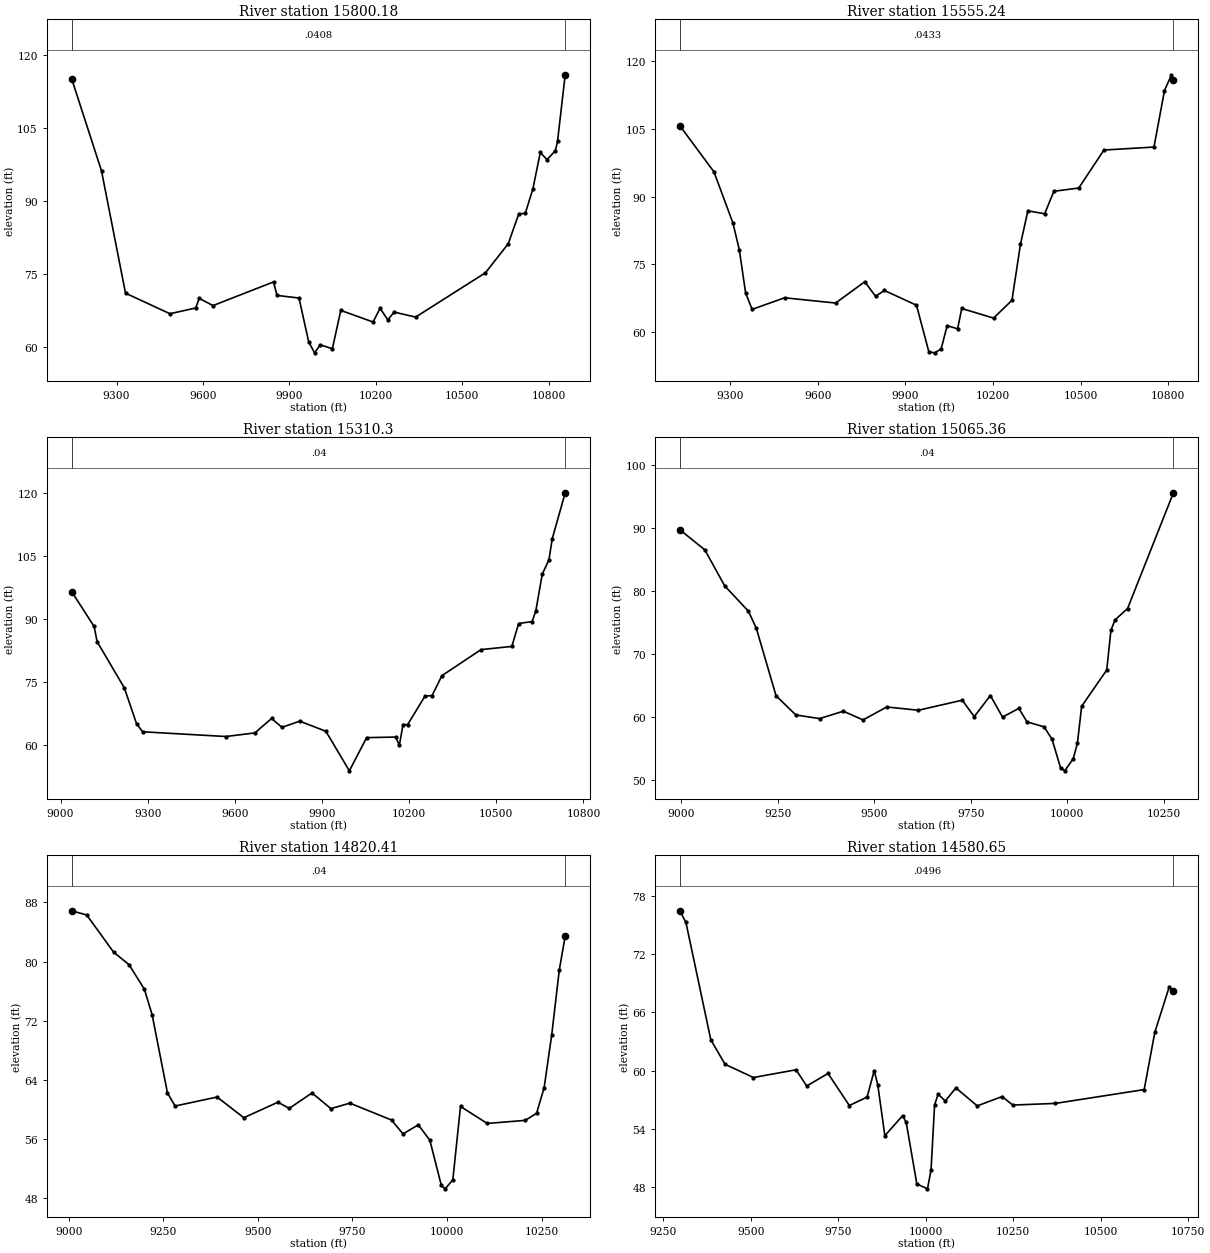
Type RM Length L Ch R = 1 ,15800.18,244.942700,244.942700,244.942700
XS GIS Cut Line= 6
900373.982913321843515.502387923900998.729730196843140.809462735
901076.743894389 843105.98450918901154.617878383843093.261062484
901213.235920247843061.999497022901826.816384909 842625.37878413
#Sta/Elev= 30
9144.317115.08099247.97896.154599331.24271.064469485.33566.846949575.07468.02292
9586.91270.019739634.81968.513479845.08973.373399857.11470.603549933.52170.06704
9967.02661.085979987.41558.8172110007.4560.4543510049.2559.6670610078.58 67.5292
10190.56 65.147310214.9367.9647510241.5865.6019910263.9267.1786210338.2466.15169
10580.7775.2574510659.7981.2166510696.43 87.354810718.83 87.4269 10745.392.46524
10771.06 99.949510794.1698.47278 10823.3100.296810830.81102.222210857.46115.8909
#Mann= 3 , 0 , 0
9144.317  0.0408       09144.317  0.0408       010857.46  0.0408       0
#XS Ineff= 2 , 0
       09824.462        10240.97       0
Bank Sta=9144.317,10857.46
Exp/Cntr=0.3,0.1

Type RM Length L Ch R = 1 ,15555.24,244.942600,244.942600,244.942600
XS GIS Cut Line= 6
900546.467737859 843730.37042088900858.259076164843596.617084923
901031.452525323843494.115173153901144.411995417843405.451109613
901491.316250302843079.157271664 901920.44312532842771.590539491
#Sta/Elev= 30
 9128.32105.69559245.04195.495639309.86684.196169331.66178.283969353.45668.66879
9375.55665.064449486.65167.630299661.41366.466789761.32171.187329797.94267.95801
 9828.2469.254989938.13365.98523 9980.3655.6963110000.4755.4479310022.5656.30834
10043.0961.4743910078.88 60.757610092.9665.2633810201.94 63.137910264.8767.06965
10293.9279.4449310319.3686.8702510376.8586.2204210408.41 91.203410493.49 91.9177
10579.56100.324510750.93100.987210786.91113.4997 10810.9116.978810817.43115.7707
#Mann= 3 , 0 , 0
 9128.32  0.0433       0 9128.32  0.0433       010817.43  0.0433       0
#XS Ineff= 2 , 0
       09831.433                       0
Bank Sta=9128.32,10817.43
Exp/Cntr=0.3,0.1

Type RM Length L Ch R = 1 , 15310.3,244.942600,244.942600,244.942600
XS GIS Cut Line= 6
900600.756154808843846.696031808901011.159586726843720.076819254
901195.313698767843638.919076036901330.307523438843552.205228096
901697.579547516 843248.30997102902063.637935159843022.563004866
#Sta/Elev= 30
9038.17596.497819115.47288.176759125.88384.556999219.58373.533469261.39365.03599
9282.31363.081919569.04661.951789668.78862.81318  9726.466.253449762.06964.14252
9823.19965.609679913.24363.204429994.15653.7712110053.3861.6830810153.3761.82169
10166.1359.88105 10178.964.7998110194.49 64.763610254.1771.56882 10278.971.71621
10312.7476.4591910447.4882.6677210553.3883.4244710576.7288.8779410623.2789.36318
10636.0791.9374810657.96100.6377   10681104.056210692.52109.101310737.04120.0481
#Mann= 3 , 0 , 0
9038.175    0.04       09038.175    0.04       010737.04    0.04       0
#XS Ineff= 2 , 0
       09817.556                       0
Bank Sta=9038.175,10737.04
Exp/Cntr=0.3,0.1

Type RM Length L Ch R = 1 ,15065.36,244.942600,244.942600,244.942600
XS GIS Cut Line= 6
900621.823951576843901.160415022901246.523500907843760.943868545
901379.439267975843725.541085805 901536.02095451843670.699237439
901644.766153205843622.272682141901845.997335954843543.348702802
#Sta/Elev= 30
8995.90489.707559060.76286.502629111.99680.808179173.47876.791259193.97274.08452
9245.20763.368019296.442 60.32689357.92359.748729419.40560.92076 9470.6459.54361
9532.121 61.59289614.09761.074079727.71362.669229758.75960.06139 9800.5863.41202
9832.125 59.98579874.23361.367759895.68159.220159939.67158.448359960.43256.46866
9982.30951.973699993.24851.4627310015.1653.3666310026.1155.8241910037.0761.70406
10102.1467.4576410112.9473.7572910123.7375.4129710156.1277.2086410274.8895.56788
#Mann= 3 , 0 , 0
8995.904    0.04       08995.904    0.04       010274.88    0.04       0
#XS Ineff= 2 , 0
       09799.318                       0
Bank Sta=8995.904,10274.88
Exp/Cntr=0.3,0.1

Type RM Length L Ch R = 1 ,14820.41,239.759900,239.759900,239.759900
XS GIS Cut Line= 6
900635.912151467843937.581203129900982.929490707843876.986838512
901221.901674391843854.450336376901395.674194426 843855.15678276
 901776.31886763843906.246285931901930.624552295843912.177788677
#Sta/Elev= 30
9007.44586.856069047.27786.29066 9118.4881.255959159.16879.580689199.85676.24698
  9220.272.811549260.74362.249669280.96760.482359392.06761.695679462.55658.90058
9552.82860.995359582.91260.162919642.96662.248439692.97560.128859743.00260.87111
9853.33758.58555  9883.656.710989924.01657.942249954.46955.871349984.92149.76208
9995.07249.2948810015.3550.5240610035.6160.4225210106.27  58.12910206.6958.54262
10236.7459.4963910256.7762.9677510276.7970.0925110296.7978.8500210312.4283.46183
#Mann= 3 , 0 , 0
9007.445    0.04       09007.445    0.04       010312.42    0.04       0
#XS Ineff= 2 , 0
       09738.272        10124.15       0
Bank Sta=9007.445,10312.42
Exp/Cntr=0.3,0.1

Type RM Length L Ch R = 1 ,14580.65,281.554400,281.554400,281.554400
XS GIS Cut Line= 2
900847.928501924843988.601334237902237.265817672844232.895207476
#Sta/Elev= 30
9297.07176.458319314.40475.258989385.47863.170779426.09260.647139507.31959.27844
 9629.1660.07662 9659.6258.406519720.54159.695319781.46156.394599832.22857.26522
9852.53559.987589862.68858.541629882.99553.281959933.762 55.35139943.91654.67038
9974.37648.3183110004.8447.8091710014.99 49.755210025.1456.46531 10035.357.56465
 10055.656.8551410086.0658.2102110146.9856.3554810218.0657.3170210248.5256.44056
10370.3656.6117810624.1958.0358910654.6563.9433910695.2768.5655110707.7268.21629
#Mann= 3 , 0 , 0
9297.071  0.0496       09297.071  0.0496       010707.72  0.0496       0
#XS Ineff= 2 , 0
       09835.582        10447.82       0
Bank Sta=9297.071,10707.72
Exp/Cntr=0.3,0.1

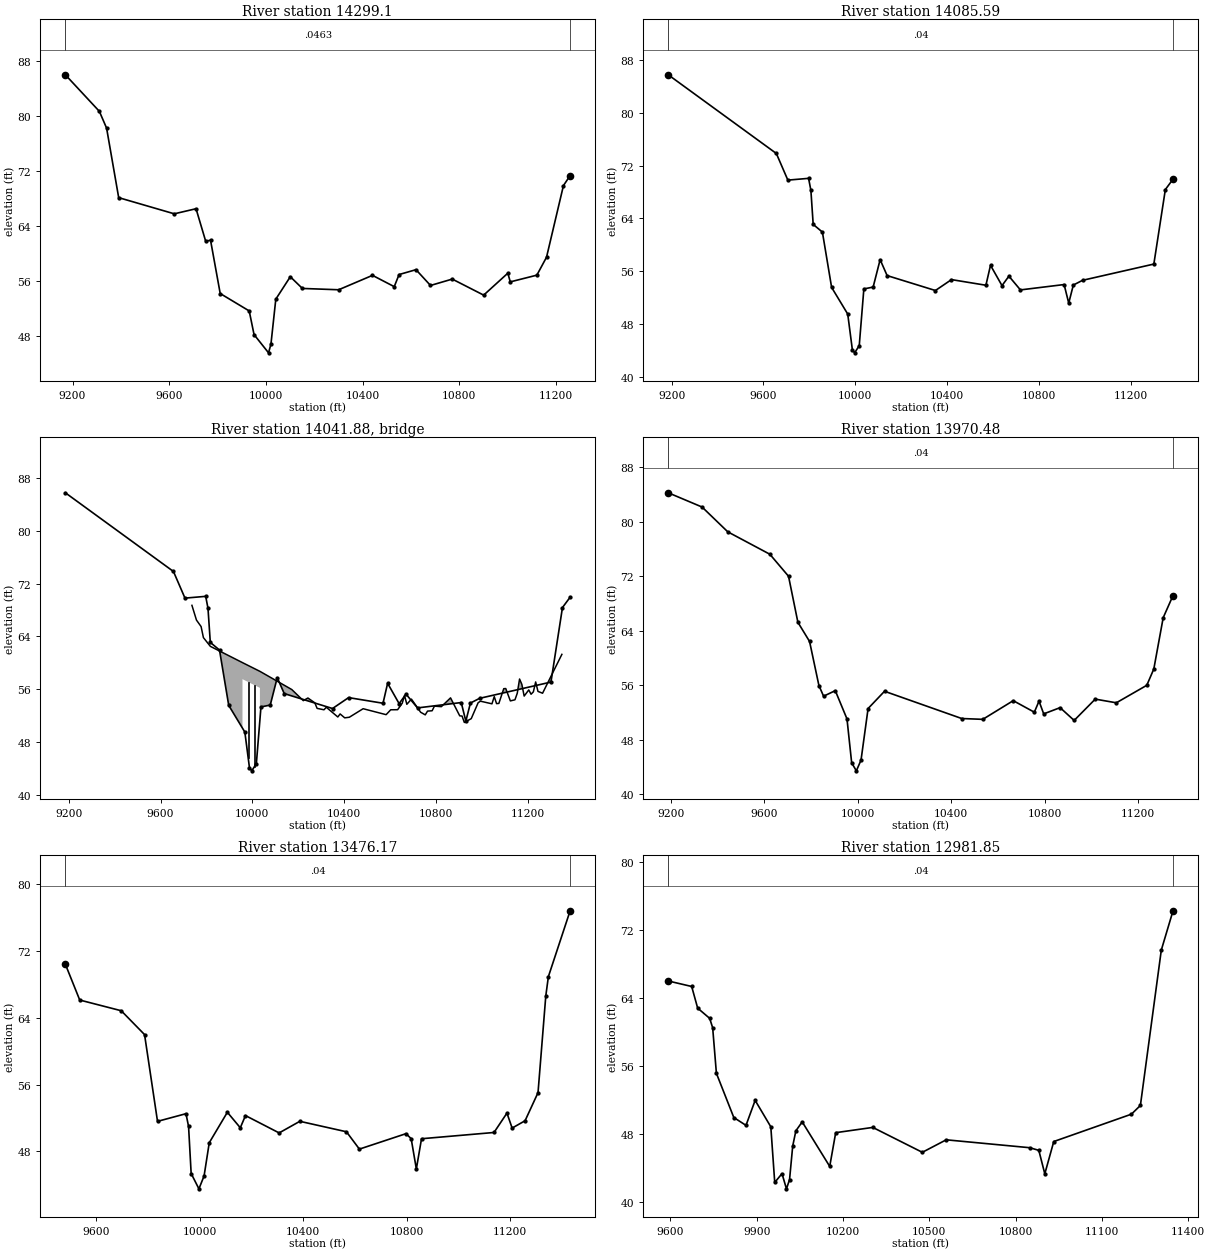
Type RM Length L Ch R = 1 , 14299.1,213.513500,213.513500,213.513500
XS GIS Cut Line= 2
900584.305307603844356.823054457902672.682930576844369.646138158
#Sta/Elev= 30
9170.35886.006499311.056 80.69659341.05678.252739391.05768.159039621.06265.80939
9711.06366.548959751.064 61.81499771.06461.981319811.06554.231049931.06751.70142
9951.06848.2669310011.07  45.61510021.0746.9047210041.0753.4119110101.0756.67066
10151.07 54.968910301.0754.7773210441.0856.8707910531.0855.2293410551.0856.98787
10621.0857.6951510681.0855.4010810771.0856.3282810901.0953.9980111001.0957.18825
11011.0955.9231411121.0956.8996211161.0959.5033811231.0969.9082911258.78  71.371
#Mann= 3 , 0 , 0
9170.358  0.0463       09170.358  0.0463       011258.78  0.0463       0
#XS Ineff= 2 , 0
       09735.931        10743.32       0
Bank Sta=9170.358,11258.78
Exp/Cntr=0.3,0.1

Type RM Length L Ch R = 1 ,14085.59,115.103900,115.103900,115.103900
XS GIS Cut Line= 6
 900554.14070511844611.317396016901021.838735508844597.308337661
901411.472840201844565.469985201901536.609464529844544.107695274
 901951.04270212844547.816092092902748.348943391844603.279420021
#Sta/Elev= 30
9185.30785.720119656.386 73.81939706.55369.791789796.85370.060669806.88668.24481
 9816.9263.098379857.05361.934899897.18653.57148 9967.4249.538989987.48644.16974
 9997.5243.6767610017.5944.7674410037.6553.3383610078.1653.6236610108.59 57.7673
10139.0355.3574610349.4953.0999910419.4954.74929 10569.553.8970410589.51 56.9136
10639.6353.84043 10669.755.2700610719.8353.1916710910.2854.0017210930.3351.19729
10950.3853.9270410990.4854.6413111301.2357.0995511351.3568.3679111384.7869.93311
#Mann= 3 , 0 , 0
9185.307    0.04       09185.307    0.04       011384.78    0.04       0
#XS Ineff= 2 , 0
       09933.376        10945.08       0
Bank Sta=9185.307,11384.78
Exp/Cntr=0.3,0.1

Type RM Length L Ch R = 3 ,14041.88,,,
BEGIN DESCRIPTION:
END DESCRIPTION:
Bridge Culvert--1,0,-1,-1, 0
Deck Dist Width WeirC Skew NumUp NumDn MinLoCord MaxHiCord MaxSubmerge Is_Ogee
45.551950,24.000000,2.6,0, 60, 60, , , 0.95, 0, 0,0,,
 9736.88 9756.63 9776.80 9786.89 9817.15 9957.11 9957.1110033.1110033.1110171.93
10222.1610242.2110272.2810282.3110312.3810322.4010372.5210382.5510402.6010422.64
10482.7910583.0310603.0810633.1510653.2010663.2210673.2410693.2910733.3910753.44
10763.4610783.5110793.5310823.6010863.7010903.8010913.8210923.8410953.9210983.99
10994.0111044.1311054.1611064.1811074.2011095.5311104.2811124.3211144.3711154.40
11164.4211174.4411184.4711204.5211214.5411224.5611234.5911244.6111264.6611348.83
   68.70   66.47   65.49   63.82   62.50   60.04   60.04   58.72   58.72   55.97
   54.29   54.69   53.96   53.12   52.91   53.29   51.82   52.28   51.69   51.78
   53.07   52.17   52.91   52.92   53.90   55.08   53.74   54.52   52.54   52.14
   52.71   52.76   53.46   53.38   54.71   51.99   51.96   50.99   51.57   53.98
   54.21   53.81   54.90   53.84   53.87   56.10   56.12   54.25   54.42   55.41
   57.56   56.75   54.98   55.91   55.26   55.62   57.12   55.69   55.41   61.29
 -931.30 -933.53 -934.51 -936.18 -937.50 -939.96   57.54   56.22 -941.28 -944.03
 -945.71 -945.31 -946.04 -946.88 -947.09 -946.71 -948.18 -947.72 -948.31 -948.22
 -946.93 -947.83 -947.09 -947.08 -946.10 -944.92 -946.26 -945.48 -947.46 -947.86
 -947.29 -947.24 -946.54 -946.62 -945.29 -948.01 -948.04 -949.01 -948.43 -946.02
 -945.79 -946.19 -945.10 -946.16 -946.13 -943.90 -943.88 -945.75 -945.58 -944.59
 -942.44 -943.25 -945.02 -944.09 -944.74 -944.38 -942.88 -944.31 -944.59 -938.71
 9736.88 9756.63 9776.80 9786.89 9817.15 9958.72 9958.7210034.7210034.7210171.93
10222.1610242.2110272.2810282.3110312.3810322.4010372.5210382.5510402.6010422.64
10482.7910583.0310603.0810633.1510653.2010663.2210673.2410693.2910733.3910753.44
10763.4610783.5110793.5310823.6010863.7010903.8010913.8210923.8410953.9210983.99
10994.0111044.1311054.1611064.1811074.2011095.5311104.2811124.3211144.3711154.40
11164.4211174.4411184.4711204.5211214.5411224.5611234.5911244.6111264.6611348.83
   68.70   66.47   65.49   63.82   62.50   60.01   60.01   58.69   58.69   55.97
   54.29   54.69   53.96   53.12   52.91   53.29   51.82   52.28   51.69   51.78
   53.07   52.17   52.91   52.92   53.90   55.08   53.74   54.52   52.54   52.14
   52.71   52.76   53.46   53.38   54.71   51.99   51.96   50.99   51.57   53.98
   54.21   53.81   54.90   53.84   53.87   56.10   56.12   54.25   54.42   55.41
   57.56   56.75   54.98   55.91   55.26   55.62   57.12   55.69   55.41   61.29
 -931.30 -933.53 -934.51 -936.18 -937.50 -939.99   57.51   56.19 -941.31 -944.03
 -945.71 -945.31 -946.04 -946.88 -947.09 -946.71 -948.18 -947.72 -948.31 -948.22
 -946.93 -947.83 -947.09 -947.08 -946.10 -944.92 -946.26 -945.48 -947.46 -947.86
 -947.29 -947.24 -946.54 -946.62 -945.29 -948.01 -948.04 -949.01 -948.43 -946.02
 -945.79 -946.19 -945.10 -946.16 -946.13 -943.90 -943.88 -945.75 -945.58 -944.59
 -942.44 -943.25 -945.02 -944.09 -944.74 -944.38 -942.88 -944.31 -944.59 -938.71
Pier Skew, UpSta & Num, DnSta & Num=  ,9981.95, 2 ,9983.56, 2 , 0 , 0 , 0 ,,
    3.00    3.00
 -940.40   59.60
    3.00    3.00
 -940.42   59.58
Pier Skew, UpSta & Num, DnSta & Num=  ,10008.28, 2 ,10009.89, 2 , 0 , 0 , 0 ,,
    3.00    3.00
 -940.85   59.15
    3.00    3.00
 -940.88   59.12
BR Coef=-1 , 0 , 0 ,, 0 ,,,0.8,0,1,0,
WSPro=,,,, 1 ,,,, 0 ,,,, 0 ,,,,-1 ,-1 ,-1 , 0 , 0 , 0 , 0 , 0
BC Design=,, 0 ,, 0 ,,,,,,

Type RM Length L Ch R = 1 ,13970.48,494.316200,494.316200,494.316200
XS GIS Cut Line= 6
900560.359974267844701.132404795900841.652622145844690.745567553
901238.011513965844691.619376889901550.839043849844667.462422351
901847.396974558844656.106576305902716.989101961844719.895538932
#Sta/Elev= 30
9188.42384.256579333.26582.161249443.30178.517749623.30875.22559 9703.3171.99027
 9743.3165.226869793.31262.410129833.31555.933199853.31754.366699903.386 55.1818
9953.47851.027129973.51544.57356 9993.55 43.399210013.5944.9759610043.7552.55472
10114.11 55.0913 10444.551.0870810534.6750.9659110665.0253.7108410755.2752.01555
10775.3253.6390810795.3751.7698710865.5652.6842310925.72 50.804711015.9653.93761
11106.2153.3966311236.5555.9689111266.6458.3674311306.7465.8971211348.8469.15945
#Mann= 3 , 0 , 0
9188.423    0.04       09188.423    0.04       011348.84    0.04       0
#XS Ineff= 2 , 0
       09940.543        10945.58       0
Bank Sta=9188.423,11348.84
Exp/Cntr=0.3,0.1

Type RM Length L Ch R = 1 ,13476.17,494.316100,494.316100,494.316100
XS GIS Cut Line= 6
900879.541592262845179.437634942901046.310916194845165.203045323
901272.353746996845149.750526946901338.377816429845148.024050159
901515.280063334 845150.36286721902829.033468896845082.257760404
#Sta/Elev= 30
9479.67970.403999535.33966.111859695.85764.830729786.06761.974489836.18451.58893
9946.29452.506879956.29650.976529966.297 45.3478  9996.343.51178 10016.345.05236
10036.3149.0303510106.3152.6768610156.3750.82158 10176.452.2823710306.5850.20581
10386.6851.5949110566.9250.3434510616.9948.2674710797.2350.1160510817.2649.51856
10837.2845.8936510857.3149.5094311137.6850.2579111187.7552.5780111207.7850.78614
11257.8451.6628911307.9155.0241711337.9566.5985511347.9668.9118311432.1176.79642
#Mann= 3 , 0 , 0
9479.679    0.04       09479.679    0.04       011432.11    0.04       0
#XS Ineff= 2 , 0
       09922.986        10896.05       0
Bank Sta=9479.679,11432.11
Exp/Cntr=0.3,0.1

Type RM Length L Ch R = 1 ,12981.85,568.671600,568.671600,568.671600
XS GIS Cut Line= 6
901076.507257496845751.224576069901268.437235475845695.763866948
901363.634030181845662.527813712901476.024722061 845614.72861862
901549.912189082845580.684632909902754.228348091845244.170179338
#Sta/Elev= 30
9592.43565.957829673.93265.310739694.73562.76279 9736.4761.560369746.90360.45069
9759.85155.095669820.35949.892389862.72748.968649894.54451.910879948.98948.79899
9962.60942.254759987.875 43.290410003.3541.50033 10014.142.5843710025.08 46.5308
10036.0948.3282910058.1149.3784610153.7544.1402510174.5248.1090810303.4748.72786
10475.6345.7977210558.6947.2690410849.42 46.337810880.5646.0258510901.3343.26701
10932.4847.0665511202.4450.2858411233.5951.3113511306.2769.59122   1134774.21781
#Mann= 3 , 0 , 0
9592.435    0.04       09592.435    0.04       0   11347    0.04       0
#XS Ineff= 2 , 0
       0                10853.33       0
Bank Sta=9592.435,11347
Exp/Cntr=0.3,0.1

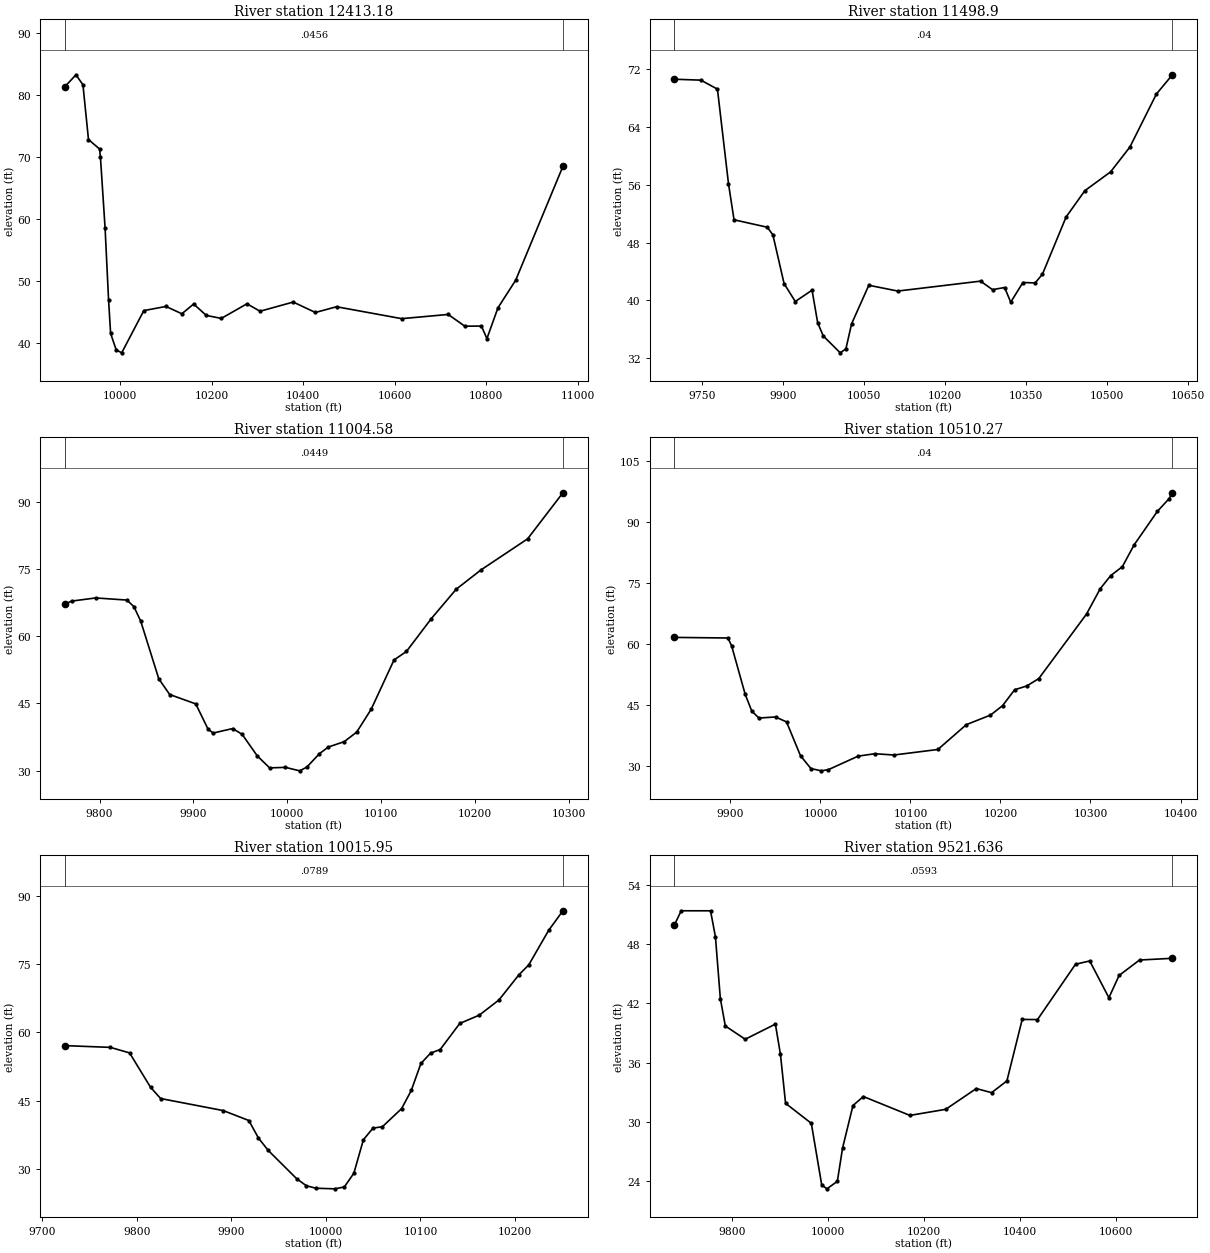
Type RM Length L Ch R = 1 ,12413.18,914.276900,914.276900,914.276900
XS GIS Cut Line= 2
901472.566211453846198.505660742902372.286603938845586.981973463
#Sta/Elev= 30
9879.39781.394669903.42283.287389918.61381.667579930.70472.833479954.88671.31204
9956.79170.046899966.978 58.5624 9974.5846.972499979.06941.54607 9991.16 38.9043
10003.2538.4126210051.6245.2281110099.9845.9018110134.6944.7174310160.4446.29466
10188.0544.4538110220.8943.96868   1027746.3277210305.5345.1249210378.0846.60968
10426.44 44.925910472.6945.85069   1061543.9295910716.6344.60867 10752.942.71628
10789.1842.7336310801.2740.7150710825.4545.6926210864.0550.1226310967.2768.50251
#Mann= 3 , 0 , 0
9879.397  0.0456       09879.397  0.0456       010967.27  0.0456       0
#XS Ineff= 2 , 0
       0                               0
Bank Sta=9879.397,10967.27
Exp/Cntr=0.3,0.1

Type RM Length L Ch R = 1 , 11498.9,494.316200,494.316200,494.316200
XS GIS Cut Line= 6
902250.463385917846482.674849264902313.195358105846220.727223971
 902374.07637529846052.222415175902477.502770517845838.239262378
902564.338793057845697.368857164902605.378611969845641.119070779
#Sta/Elev= 30
9699.11570.635879747.90970.508779778.61369.263739799.08256.161169809.31751.16878
9870.86950.138439881.23149.086939901.95442.338169922.67839.853159953.76341.42074
9964.12536.917839974.53535.0787910005.8932.7435110016.39 33.296710026.9336.75981
10058.8142.1011510112.4641.30008 10265.642.6737910287.7741.49528 10310.241.79119
10321.4939.7574910344.0842.4837810366.6742.4236310380.2143.6345110424.0551.56545
10458.7555.2042510506.3257.8039410542.0461.2399710591.1968.5909110620.75 71.2522
#Mann= 3 , 0 , 0
9699.115    0.04       09699.115    0.04       010620.75    0.04       0
#XS Ineff= 2 , 0
       0                               0
Bank Sta=9699.115,10620.75
Exp/Cntr=0.3,0.1

Type RM Length L Ch R = 1 ,11004.58,494.316100,494.316100,494.316100
XS GIS Cut Line= 6
902571.286675446846580.008029605902578.631012481846572.485248445
902631.247162156846524.194969433902744.719599196846427.754244654
902921.264457911846273.858129845902969.744197124846229.641219978
#Sta/Elev= 30
9763.17267.176249770.17167.855939795.90468.564319829.12368.087879836.623 66.6191
9843.912 63.36379863.15250.501829874.74347.005359902.52344.912319915.64739.27883
9921.06738.403269941.89439.40707 9951.95 38.12039968.14233.291519981.26630.62444
9998.18430.7402210013.3529.9669210020.9930.8123210034.2533.78089 10043.835.27917
10060.7736.4816110074.0438.6075110089.4743.6974410113.8254.7141510127.0856.61461
10153.6163.9512610180.1370.5120810206.66 74.836610256.2181.7527910293.8492.03918
#Mann= 3 , 0 , 0
9763.172  0.0449       09763.172  0.0449       010293.84  0.0449       0
#XS Ineff= 2 , 0
       0                               0
Bank Sta=9763.172,10293.84
Exp/Cntr=0.3,0.1

Type RM Length L Ch R = 1 ,10510.27,494.316200,494.316200,494.316200
XS GIS Cut Line= 6
902890.396984744846936.713115144902971.064769104846866.152527308
903013.854954324 846830.12192287903059.075401321846791.710612372
903242.907601151 846627.56774253903307.859620882846573.978915636
#Sta/Elev= 30
9837.88761.607629897.14661.461249901.24559.614529916.43347.619389923.71743.52522
9931.62241.808249950.20742.067319962.36540.847149977.88232.533949989.44229.39983
   1000128.8366810008.91 29.134310041.8632.4425710060.3333.0382610081.6832.72565
10130.4634.0810110162.1240.1843210188.9342.5268410202.3444.8458310215.7448.75315
10229.1549.6744310242.5651.4924510295.62 67.346710310.8273.5590810322.46 76.7876
10335.4278.9806510348.3984.2997310374.3292.5710910387.2895.6677510390.99 97.1266
#Mann= 3 , 0 , 0
9837.887    0.04       09837.887    0.04       010390.99    0.04       0
#XS Ineff= 2 , 0
       0                               0
Bank Sta=9837.887,10390.99
Exp/Cntr=0.3,0.1

Type RM Length L Ch R = 1 ,10015.95,494.316200,494.316200,494.316200
XS GIS Cut Line= 6
903060.874260828 847250.70726106903173.612638247847207.112880204
903220.697466692847194.400677372903402.802316285847168.764421742
903446.074265476847159.961766054903569.167216764847122.891601039
#Sta/Elev= 30
9724.21257.104679772.14456.723479792.47655.510319814.70747.956989825.33945.50069
  9891.642.855149918.59940.677479928.76236.829149938.92534.156639969.14527.91738
9979.21626.394719989.28725.8309410009.4325.6936310019.53 26.106610029.6229.11615
10039.7136.46684 10049.838.9965110059.8939.33787 10080.143.2852610090.3147.26492
10100.5153.1875110110.7255.4596210120.9256.2569310141.5861.9642210162.2563.79565
10183.0567.1246710204.0172.6089410214.4974.8016910235.5882.3885110250.6486.68463
#Mann= 3 , 0 , 0
9724.212  0.0789       09724.212  0.0789       010250.64  0.0789       0
#XS Ineff= 2 , 0
       0                               0
Bank Sta=9724.212,10250.64
Exp/Cntr=0.3,0.1

Type RM Length L Ch R = 1 ,9521.636,494.316100,494.316100,494.316100
XS GIS Cut Line= 6
903131.154189811 847746.10603398903222.890875979847729.104992437
903291.856512833847710.570076241903347.226985536 847692.21298383
903619.368396844 847582.58090572904109.136226672847405.823782759
#Sta/Elev= 30
9680.37249.943789694.34451.35955 9755.4651.356719765.65548.729669775.88342.47509
9786.23739.701599827.65738.354739890.56439.887849901.09936.820629911.77531.87144
9965.38929.845919987.07923.603099997.924 23.214710019.6223.9752310030.4627.33514
10052.1531.6478810073.8432.5587510170.73 30.646810245.3431.2631610309.0833.36544
10340.9532.9493310372.8234.1382410404.6940.3619210436.5540.3462810515.7345.94738
10545.37 46.281710585.2842.5571710606.5244.8120110649.0646.3743210717.5646.54891
#Mann= 3 , 0 , 0
9680.372  0.0593       09680.372  0.0593       010717.56  0.0593       0
#XS Ineff= 2 , 0
       0                               0
Bank Sta=9680.372,10717.56
Exp/Cntr=0.3,0.1