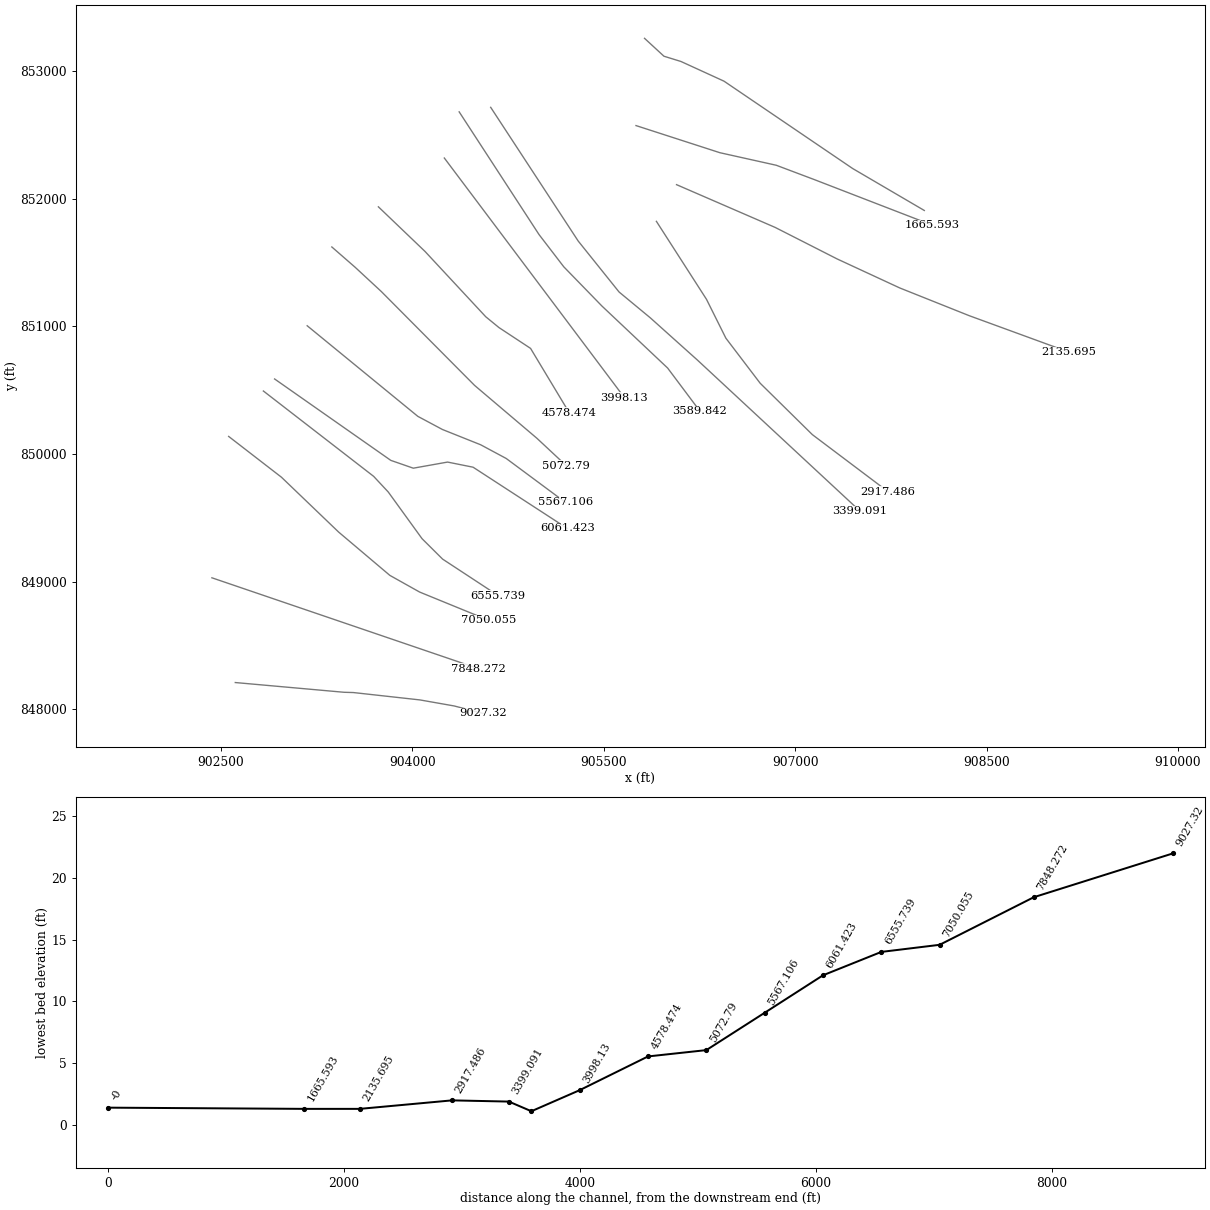
HEC-RAS study 16701_ras.prj: 16701

--- 16701_ras.g01 (geometry) --- (continued)

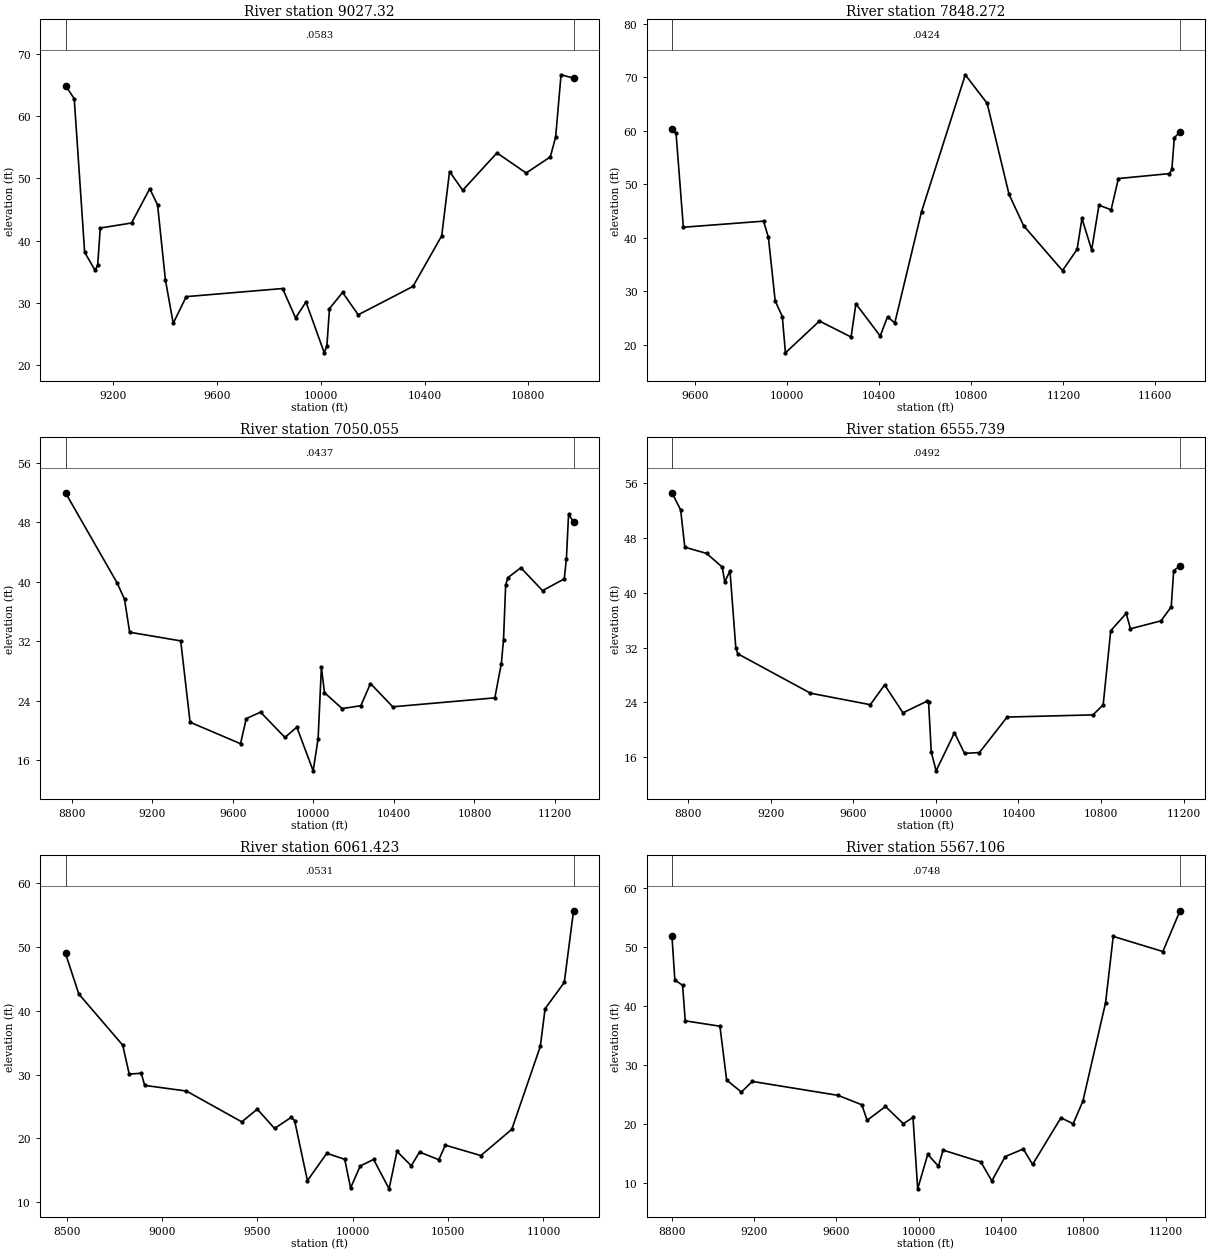
Type RM Length L Ch R = 1 , 9027.32,1179.047800,1179.047800,1179.047800
XS GIS Cut Line= 6
902611.488505488848209.174734252903464.146500769848132.911804983
 903537.28025529848130.760481112904059.002783354848073.007057197
904326.903493749 848025.83217875904551.593298013847967.660642508
#Sta/Elev= 30
 9015.7764.857179049.41562.747099089.57538.136499129.73435.226249139.77436.06013
9149.81442.015949270.29342.822289340.57248.328649370.69245.718479400.81233.71638
9430.93226.733389481.13131.012739852.60832.31346 9902.69 27.59739942.77630.15901
10013.24 22.000210023.3223.09778 10033.429.0939910083.7931.6876910144.2128.10318
10355.2232.6514710465.9740.7667610496.3151.0741310546.9248.0682910678.9554.06262
10791.4850.8437710884.5253.4141410905.2456.6138310925.9666.5913510974.2266.06072
#Mann= 3 , 0 , 0
 9015.77  0.0583       0 9015.77  0.0583       010974.22  0.0583       0
#XS Ineff= 2 , 0
       09662.877        10078.29       0
Bank Sta=9015.77,10974.22
Exp/Cntr=0.3,0.1

Type RM Length L Ch R = 1 ,7848.272,798.216900,798.216900,798.216900
XS GIS Cut Line= 2
902428.216050207849029.598168501904518.493827985848317.792612945
#Sta/Elev= 30
9498.90860.348729516.63959.496419548.33141.93928 9896.9443.074779918.067 40.0274
9947.478 28.1532  9978.525.242739992.01518.4478410139.9124.3926810277.2421.40837
10298.3727.6189510404.0121.59044 10435.725.1910610467.3924.0393410583.5944.84869
10773.7470.4498910868.8265.1113210963.89  48.09411027.2842.22634 11196.333.82655
11259.6837.7978411280.8143.5744511323.0737.6999411354.7646.0601411407.5845.20157
11439.2751.0445411661.1151.9672711671.6852.7496611682.2458.6711511707.0659.75898
#Mann= 3 , 0 , 0
9498.908  0.0424       09498.908  0.0424       011707.06  0.0424       0
#XS Ineff= 2 , 0
       09916.224                       0
Bank Sta=9498.908,11707.06
Exp/Cntr=0.3,0.1

Type RM Length L Ch R = 1 ,7050.055,494.316100,494.316100,494.316100
XS GIS Cut Line= 6
 902559.45122093850136.980796998902973.518895845849817.212384483
903421.310820465 849387.97597289903823.082887702849048.476575547
904056.270312194848917.986420326904597.986669164848696.566283827
#Sta/Elev= 30
8769.165 51.99279025.43439.863989062.16937.676579087.71333.233719341.21932.07045
9387.82521.127219638.358 18.23739666.715 21.61729737.60822.483969858.85819.08199
9917.85420.47095    999914.5887810023.5618.92429 10039.9 28.541210055.1325.10487
10142.8922.96473 10235.723.3495810283.57 26.332910394.0923.2036910901.1224.40452
10933.4329.02269 10944.232.1947310954.9739.5924910965.7440.5693511030.35 41.9058
11138.0438.8299711245.7440.40762 11256.543.0803211267.2749.0719311292.0348.09424
#Mann= 3 , 0 , 0
8769.165  0.0437       08769.165  0.0437       011292.03  0.0437       0
#XS Ineff= 2 , 0
       0                10045.08       0
Bank Sta=8769.165,11292.03
Exp/Cntr=0.3,0.1

Type RM Length L Ch R = 1 ,6555.739,494.316200,494.316200,494.316200
XS GIS Cut Line= 6
902831.637039537850492.737752342903695.941491608849824.234819212
903810.457279991849701.653586912904075.617627944 849335.62087824
904236.395899623849176.056165751904672.272351517848890.067710368
#Sta/Elev= 30
 8721.16 54.58618763.14552.088588783.32246.649628888.98845.731828964.51643.75751
8977.07941.587079002.248 43.20099030.40532.001989040.00131.091769392.36225.34266
9682.30123.663649751.53526.557789840.56422.479439957.38324.182539964.68923.99366
9977.57616.77218   1000114.0131110090.1819.5672110138.8116.5614410210.97 16.6822
10345.2721.8614310761.1722.1784610810.6623.63781 10847.434.4650510922.32  36.991
 10942.834.7376911090.8635.8999311140.35 37.936411152.4143.2345711183.04  43.912
#Mann= 3 , 0 , 0
 8721.16  0.0492       0 8721.16  0.0492       011183.04  0.0492       0
#XS Ineff= 2 , 0
       09891.229        10254.14       0
Bank Sta=8721.16,11183.04
Exp/Cntr=0.3,0.1

Type RM Length L Ch R = 1 ,6061.423,494.316200,494.316200,494.316200
XS GIS Cut Line= 6
902919.535884513850587.078785536903830.236464667849949.475209851
904006.725399837849888.239786339904275.437070934849936.098205937
904475.409822554849895.884324274905213.505638017849416.396820934
#Sta/Elev= 30
8493.87148.94167 8563.4542.605518793.86834.592318827.916 30.06388890.869  30.204
8909.07628.301219127.98227.417179418.00322.597219499.37624.580899590.07721.56429
9678.14723.320049695.15322.790519762.23113.391589863.75617.675979957.87916.73571
9988.566 12.257510039.1315.6931310109.1916.7200110190.3812.1171310231.9117.98779
 10306.715.7186610350.1417.8782710451.2216.6727510485.3518.9516110671.5817.32191
10833.8121.4281310983.3634.4024111008.43 40.298611109.0144.4087311157.6155.61996
#Mann= 3 , 0 , 0
8493.871  0.0531       08493.871  0.0531       011157.61  0.0531       0
#XS Ineff= 2 , 0
       09638.668        10450.11       0
Bank Sta=8493.871,11157.61
Exp/Cntr=0.3,0.1

Type RM Length L Ch R = 1 ,5567.106,494.316100,494.316100,494.316100
XS GIS Cut Line= 6
903175.023202971851003.834648701 904042.36959991850294.134212365
904234.936693367850191.329965414904534.576784931850071.680745151
904735.026438272849964.222893469905199.345218172849620.006389426
#Sta/Elev= 30
8801.57851.826758815.55544.409828853.16743.519638866.07137.507379034.53536.59684
9067.17927.474039138.78225.459619191.95327.253529607.893 24.90019723.97523.30132
9749.61320.671689838.80423.016699925.53520.090679972.413 21.1628 9995.31  9.0791
10044.0814.9032310096.1412.9137210118.5515.6337410302.0113.6341110355.4710.41393
10420.4414.5416710508.5315.8206110553.4213.2009910691.1621.1023510750.45 20.0869
10798.0223.9341810908.1440.58365 10945.251.7944811186.36 49.235511269.67 56.1301
#Mann= 3 , 0 , 0
8801.578  0.0748       08801.578  0.0748       011269.67  0.0748       0
#XS Ineff= 2 , 0
       09965.942        10709.24       0
Bank Sta=8801.578,11269.67
Exp/Cntr=0.3,0.1

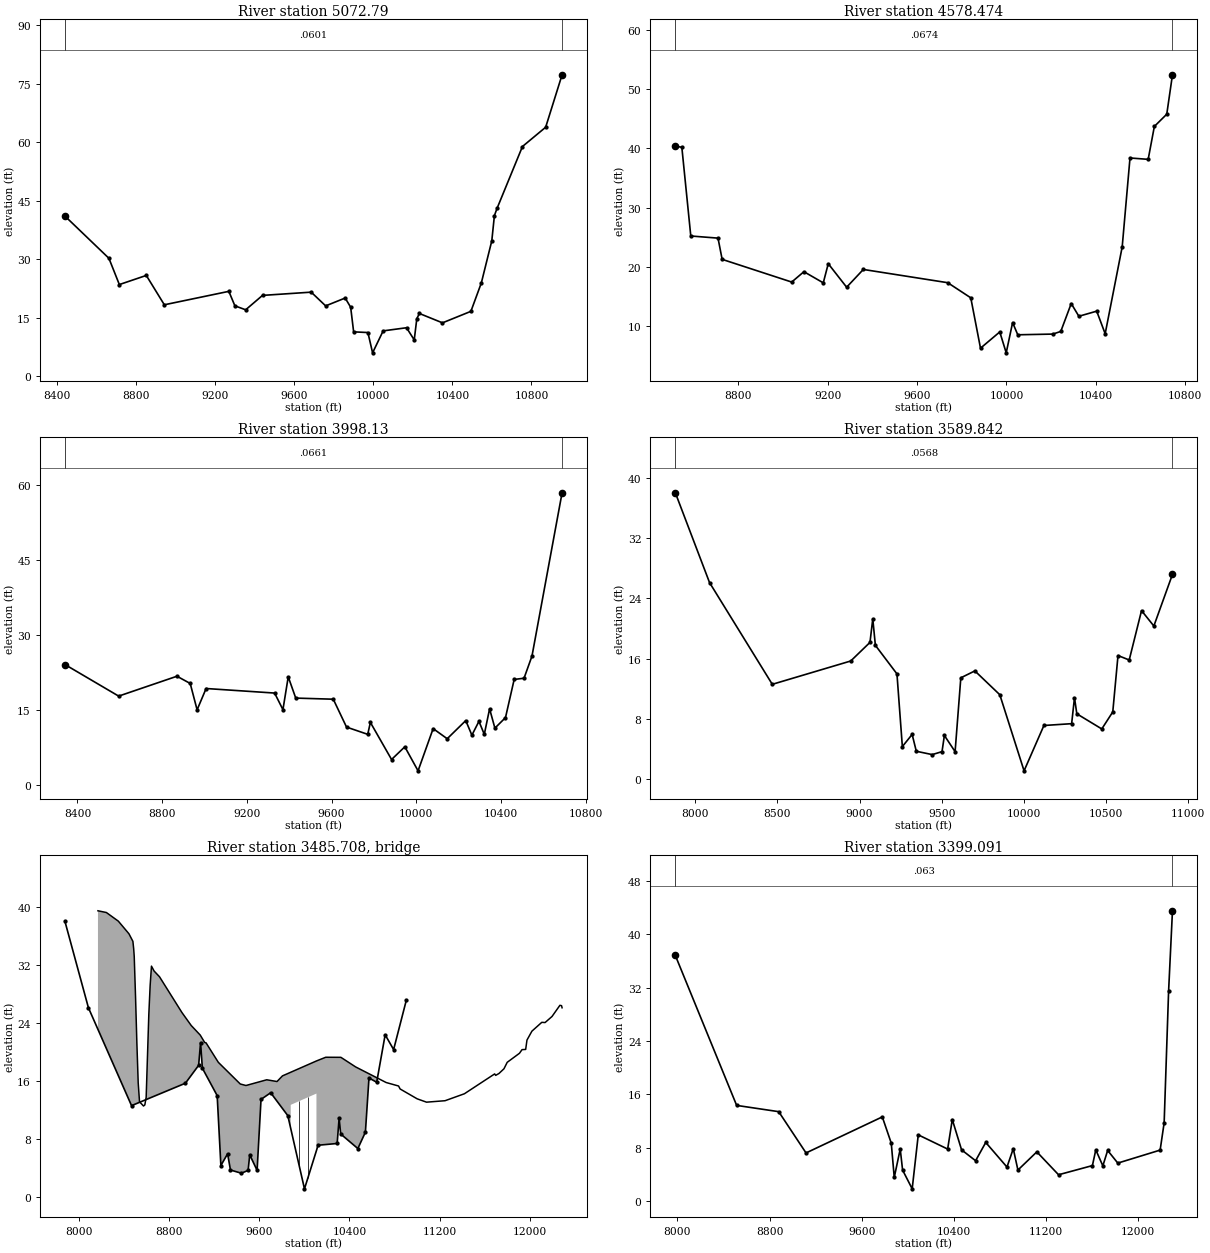
Type RM Length L Ch R = 1 , 5072.79,494.316200,494.316200,494.316200
XS GIS Cut Line= 6
903368.202355968 851620.97121719903551.467757396851461.401345001
 903756.00528388851271.968094809904486.803278848850536.882755107
904975.152304083850122.866529052905206.007582439849907.613697025
#Sta/Elev= 30
8440.54141.105468662.86530.292268715.618 23.55548851.91825.898778943.14918.37082
9269.43421.81575    930018.103469354.566  17.0869439.678 20.77869686.00321.61107
9759.11118.090069857.87820.104019885.60317.74439 9900.6411.430799972.83911.25669
  9996.56.05126610049.9211.68162 10168.212.4855510207.159.36155210220.1414.79511
10233.1216.14417   1035013.7421210493.7616.69117 10546.623.9875710599.4434.77742
10612.6641.2412710625.8743.0706410754.4458.9487910871.8863.8956410954.9377.34348
#Mann= 3 , 0 , 0
8440.541  0.0601       08440.541  0.0601       010954.93  0.0601       0
#XS Ineff= 2 , 0
       0 9837.47                       0
Bank Sta=8440.541,10954.93
Exp/Cntr=0.3,0.1

Type RM Length L Ch R = 1 ,4578.474,580.344100,580.344100,580.344100
XS GIS Cut Line= 6
 903733.16910736851935.380159553904098.596142582851585.944385645
904574.516304993851074.435388364904677.748706131850989.950638655
904925.964577822850826.464869463905228.856084176 850323.07143086
#Sta/Elev= 30
8518.33640.400588547.44640.180048587.44825.234698709.31324.874988727.75321.29777
 9039.08 17.46999093.71519.216919180.35717.337599202.64720.564499284.908 16.5996
9359.58819.595489737.40317.360479840.44314.812979883.9516.3203849970.1729.063059
    99995.53845810027.6110.6422610050.738.58139510207.688.700698 10243.29.145945
10289.9513.8463810324.1711.7033210404.0212.5649110441.878.754299 10518.123.41393
10552.9438.3866310634.3238.1558110661.9743.7051210717.5145.7683810743.0152.41122
#Mann= 3 , 0 , 0
8518.336  0.0674       08518.336  0.0674       010743.01  0.0674       0
#XS Ineff= 2 , 0
       09785.143                       0
Bank Sta=8518.336,10743.01
Exp/Cntr=0.3,0.1

Type RM Length L Ch R = 1 , 3998.13,408.288200,408.288200,408.288200
XS GIS Cut Line= 2
904249.892772779852317.716223422905660.999663806850441.426246646
#Sta/Elev= 30
8340.86624.060928594.513 17.74668869.787 21.7233 8932.3520.276578964.94215.00528
9007.42419.266949330.96218.357429370.28515.03834 9395.3121.601739430.78617.34977
9608.02217.127489670.58411.551199770.68410.100579783.19612.487189883.2965.066853
9945.8587.60807310008.422.79874310079.6411.2459410146.069.22197910233.6412.85025
10262.659.93219810295.9212.7009110321.2310.0995410346.2615.2065410371.2811.34083
10421.3313.44793 10462.321.0801810508.9221.3257710546.4625.7652610688.5658.42027
#Mann= 3 , 0 , 0
8340.866  0.0661       08340.866  0.0661       010688.56  0.0661       0
#XS Ineff= 2 , 0
       09567.074                       0
Bank Sta=8340.866,10688.56
Exp/Cntr=0.3,0.1

Type RM Length L Ch R = 1 ,3589.842,190.750400,190.750400,190.750400
XS GIS Cut Line= 6
904366.287620241852679.326411852 904992.44444071851717.880876345
 905186.27258569 851465.53111284905485.317318755851158.226341994
 906000.30641536850672.532830729906253.815720961850334.407249258
#Sta/Elev= 30
 7879.07 38.00448087.10726.084418468.98812.579158946.338 15.67549063.465  18.144
9080.507 21.27519096.29817.75522 9227.6313.963379260.4634.3141719320.0855.930379
 9345.373.6933099442.2923.2509089501.8333.6434549516.291 5.787619581.4773.641236
9616.21613.442319701.72714.359179853.52711.1973610001.141.09497410121.917.114456
10290.667.35563410307.9910.8062610322.178.66386510474.09 6.6563610540.998.918029
10572.7616.3996910640.9815.8087110715.9722.3618410790.9620.3191210904.1927.17484
#Mann= 3 , 0 , 0
 7879.07  0.0568       0 7879.07  0.0568       010904.19  0.0568       0
#XS Ineff= 2 , 0
       09835.082        10156.74       0
Bank Sta=7879.07,10904.19
Exp/Cntr=0.3,0.1

Type RM Length L Ch R = 3 ,3485.708,,,
BEGIN DESCRIPTION:
END DESCRIPTION:
Bridge Culvert--1,0,-1,-1, 0
Deck Dist Width WeirC Skew NumUp NumDn MinLoCord MaxHiCord MaxSubmerge Is_Ogee
52.375200,86.000000,2.6,0, 60, 60, , , 0.95, 0, 0,0,,
 8171.40 8246.09 8351.82 8445.79 8481.03 8488.10 8492.78 8504.52 8516.27 8528.02
 8539.76 8575.00 8586.75 8598.50 8621.99 8633.74 8645.49 8668.98 8716.81 8915.66
 8997.89 9077.61 9117.00 9129.08 9237.88 9432.18 9482.71 9666.72 9757.89 9806.15
 9879.28 9879.2810107.2810107.2810189.3410323.7510455.0610724.9410834.8010848.54
10999.6011082.4211246.8011417.9911686.2711695.1911724.3711768.6711797.3211906.00
11928.6311960.9311972.4012016.1712103.7112132.8912194.4012264.2012278.7812283.50
   39.48   39.24   38.05   36.31   35.26   34.21   33.19   27.57   21.21   15.73
   13.11   12.53   12.68   13.73   25.17   29.14   31.84   31.16   30.37   25.43
   23.64   22.32   21.30   21.25   18.56   15.57   15.36   16.15   15.91   16.69
   17.19   17.19   18.75   18.75   19.26   19.25   17.92   15.77   15.29   14.88
   13.52   13.06   13.26   14.22   16.96   16.76   17.02   17.67   18.56   19.81
   20.31   20.34   21.63   22.86   24.08   24.05   24.89   26.43   26.38   26.09
 -960.52 -960.76 -961.95 -963.69 -964.74 -965.79 -966.81 -972.43 -978.79 -984.27
 -986.89 -987.47 -987.32 -986.27 -974.83 -970.86 -968.16 -968.84 -969.63 -974.57
 -976.36 -977.68 -978.70 -978.75 -981.44 -984.43 -984.64 -983.85 -984.09 -983.31
 -982.81   12.69   14.25 -981.25 -980.74 -980.75 -982.08 -984.23 -984.71 -985.12
 -986.48 -986.94 -986.74 -985.78 -983.04 -983.24 -982.98 -982.33 -981.44 -980.19
 -979.69 -979.66 -978.37 -977.14 -975.92 -975.95 -975.11 -973.57 -973.62 -973.91
 8171.40 8246.09 8351.82 8445.79 8481.03 8488.10 8492.78 8504.52 8516.27 8528.02
 8539.76 8575.00 8586.75 8598.50 8621.99 8633.74 8645.49 8668.98 8716.81 8915.66
 8997.89 9077.61 9117.00 9129.08 9237.88 9432.18 9482.71 9666.72 9757.89 9806.15
 9842.62 9842.6210070.6210070.6210189.3410323.7510455.0610724.9410834.8010848.54
10999.6011082.4211246.8011417.9911686.2711695.1911724.3711768.6711797.3211906.00
11928.6311960.9311972.4012016.1712103.7112132.8912194.4012264.2012278.7812283.50
   39.48   39.24   38.05   36.31   35.26   34.21   33.19   27.57   21.21   15.73
   13.11   12.53   12.68   13.73   25.17   29.14   31.84   31.16   30.37   25.43
   23.64   22.32   21.30   21.25   18.56   15.57   15.36   16.15   15.91   16.69
   16.94   16.94   18.50   18.50   19.26   19.25   17.92   15.77   15.29   14.88
   13.52   13.06   13.26   14.22   16.96   16.76   17.02   17.67   18.56   19.81
   20.31   20.34   21.63   22.86   24.08   24.05   24.89   26.43   26.38   26.09
 -960.52 -960.76 -961.95 -963.69 -964.74 -965.79 -966.81 -972.43 -978.79 -984.27
 -986.89 -987.47 -987.32 -986.27 -974.83 -970.86 -968.16 -968.84 -969.63 -974.57
 -976.36 -977.68 -978.70 -978.75 -981.44 -984.43 -984.64 -983.85 -984.09 -983.31
 -983.06   12.44   14.00 -981.50 -980.74 -980.75 -982.08 -984.23 -984.71 -985.12
 -986.48 -986.94 -986.74 -985.78 -983.04 -983.24 -982.98 -982.33 -981.44 -980.19
 -979.69 -979.66 -978.37 -977.14 -975.92 -975.95 -975.11 -973.57 -973.62 -973.91
Pier Skew, UpSta & Num, DnSta & Num=  ,9954.62, 2 ,9917.95, 2 , 0 , 0 , 0 ,,
    4.00    4.00
 -982.29   17.71
    4.00    4.00
 -982.55   17.45
Pier Skew, UpSta & Num, DnSta & Num=  ,10031.95, 2 ,9995.29, 2 , 0 , 0 , 0 ,,
    4.00    4.00
 -981.76   18.24
    4.00    4.00
 -982.02   17.98
BR Coef=-1 , 0 , 0 ,, 0 ,,,0.8,0,1,0,
WSPro=,,,, 1 ,,,, 0 ,,,, 0 ,,,,-1 ,-1 ,-1 , 0 , 0 , 0 , 0 , 0
BC Design=,, 0 ,, 0 ,,,,,,

Type RM Length L Ch R = 1 ,3399.091,481.605700,481.605700,481.605700
XS GIS Cut Line= 6
904613.374174028852714.695484228905299.205828124851667.479030052
905619.699942813851268.184413007905865.256476493851065.186121251
906234.108701958850734.683707204907507.917152673849552.159654158
#Sta/Elev= 30
7982.00736.806328514.295 14.36558879.34413.428379116.6267.2491549778.65112.64525
9856.499 8.717019882.4483.5865919934.3477.8367329954.8554.68662310038.141.877621
10090.949.95631610346.057.83321210386.3312.2476810466.897.71287710588.626.084639
10676.818.82329610861.095.13772110915.677.88761110956.074.68954711120.347.412657
11308.833.98470911602.795.35866711632.197.71079811693.42 5.3171111735.077.624269
11823.265.73095312190.717.67517112225.5711.75505 12264.231.4454712297.78 43.4956
#Mann= 3 , 0 , 0
7982.007   0.063       07982.007   0.063       012297.78   0.063       0
#XS Ineff= 2 , 0
       09796.704         10115.9       0
Bank Sta=7982.007,12297.78
Exp/Cntr=0.3,0.1

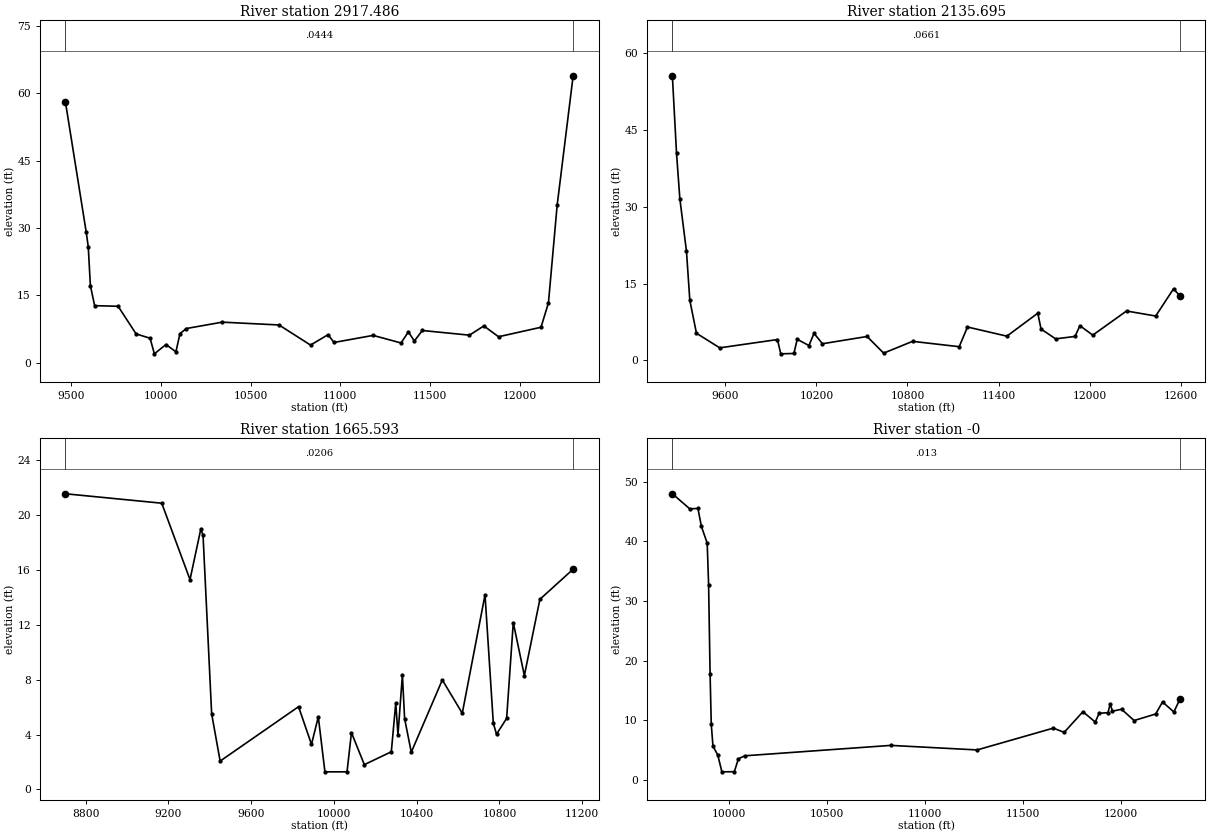
Type RM Length L Ch R = 1 ,2917.486,781.790600,781.790600,781.790600
XS GIS Cut Line= 6
905912.147541646  851821.7171567906305.078516823851210.481101932
906456.694312478850906.644957162906725.648020946850553.547307702
907134.808765823850150.923234316907728.726649006849703.813844263
#Sta/Elev= 30
9468.40257.95564 9583.3829.199119595.26825.848159607.15617.164059630.93212.69942
  9761.712.561579862.0266.4081789940.021 5.447939963.7971.97604610028.464.053528
10083.942.42162510106.456.46689410142.127.61096610341.85 9.0269810658.578.402091
10834.17 3.9262110932.236.24395610964.774.504061 11183.26.08074311338.734.393011
11379.676.86122411412.894.832493 11457.57.17078311719.986.13162611800.268.189116
11882.225.77913812118.927.89208712160.3313.3079812208.7834.9964312298.0863.85741
#Mann= 3 , 0 , 0
9468.402  0.0444       09468.402  0.0444       012298.08  0.0444       0
#XS Ineff= 2 , 0
       09862.335        10286.63       0
Bank Sta=9468.402,12298.08
Exp/Cntr=0.3,0.1

Type RM Length L Ch R = 1 ,2135.695,470.102500,470.102500,470.102500
XS GIS Cut Line= 6
906070.066890673852109.030722116 906843.31675823851773.993744054
907328.604278724851527.304724897907819.794742653 851299.90979591
908364.153004109 851082.71455088909145.031242771850797.498754995
#Sta/Elev= 30
9250.294 55.6315 9277.61 40.52989299.52231.611119343.346   21.319365.25811.76177
9409.0825.3053499562.4662.4605189942.9964.0807399964.5791.287071 10051.41.358591
10073.174.13424410150.542.90578810183.885.29251110239.513.25976310533.644.678694
10642.821.42332910833.543.72893811140.892.68217811195.356.53206411454.984.740457
11658.789.23166411680.216.13789311776.574.21191211904.464.69022911936.336.792238
12021.164.94129112243.829.66042612436.02 8.67664 12553.614.0015912596.3912.57739
#Mann= 3 , 0 , 0
9250.294  0.0661       09250.294  0.0661       012596.39  0.0661       0
#XS Ineff= 2 , 0
       09445.265        10792.86       0
Bank Sta=9250.294,12596.39
Exp/Cntr=0.3,0.1

Type RM Length L Ch R = 1 ,1665.593,1665.592700,1665.592700,1665.592700
XS GIS Cut Line= 5
905752.236496286852571.768618115906409.972064999852359.243961036
906851.831295284852260.973618733907148.945499683852149.109211197
908074.993607366851791.544486684
#Sta/Elev= 30
8702.29321.561249167.596 20.87419304.21415.302089356.75919.012739367.268 18.5217
9408.9065.5119979449.8842.0700369828.9246.037182  9891.53.2879119924.3495.297783
9956.4051.28707110063.261.28721110084.634.14651310146.921.81054410277.332.749816
10298.776.30225910309.493.98552310330.938.34239210341.645.166874 10373.82.716557
10523.887.98777110620.355.558164 10730.314.1929610770.434.82821810785.824.032323
10834.74  5.1807 10866.912.16858 10920.58.30970310995.5413.8669911156.3216.06327
#Mann= 3 , 0 , 0
8702.293  0.0206       08702.293  0.0206       011156.32  0.0206       0
#XS Ineff= 2 , 0
       0                 10344.7       0
Bank Sta=8702.293,11156.32
Exp/Cntr=0.3,0.1

Type RM Length L Ch R = 1 ,      -0,0.000000,0.000000,0.000000
XS GIS Cut Line= 6
905819.142802918853255.179450979905971.383739531853115.071027353
906104.961587855853073.778460269906442.300077946852919.562716313
907450.385512676852235.489785922908012.070058132851906.791091949
#Sta/Elev= 30
9713.55247.98859 9802.4245.459669843.82545.529639861.48942.514069891.02339.71284
9898.18632.77333 9905.7917.738429911.7779.3508019920.452 5.694039945.0344.193339
9965.8571.38549610029.281.407649   100503.56768110082.364.07245510826.535.818215
11266.425.05742411655.088.714837 11710.18.000441 11805.711.4639411868.499.728677
11888.2911.1998411933.1511.2930711944.7412.7635811956.3211.5539712002.6711.87774
12066.489.98346812176.4711.0822812211.23 13.098612269.1611.4150512300.5213.61233
#Mann= 3 , 0 , 0
9713.552   0.013       09713.552   0.013       012300.52   0.013       0
#XS Ineff= 2 , 0
       0                11417.38       0
Bank Sta=9713.552,12300.52
Exp/Cntr=0.3,0.1